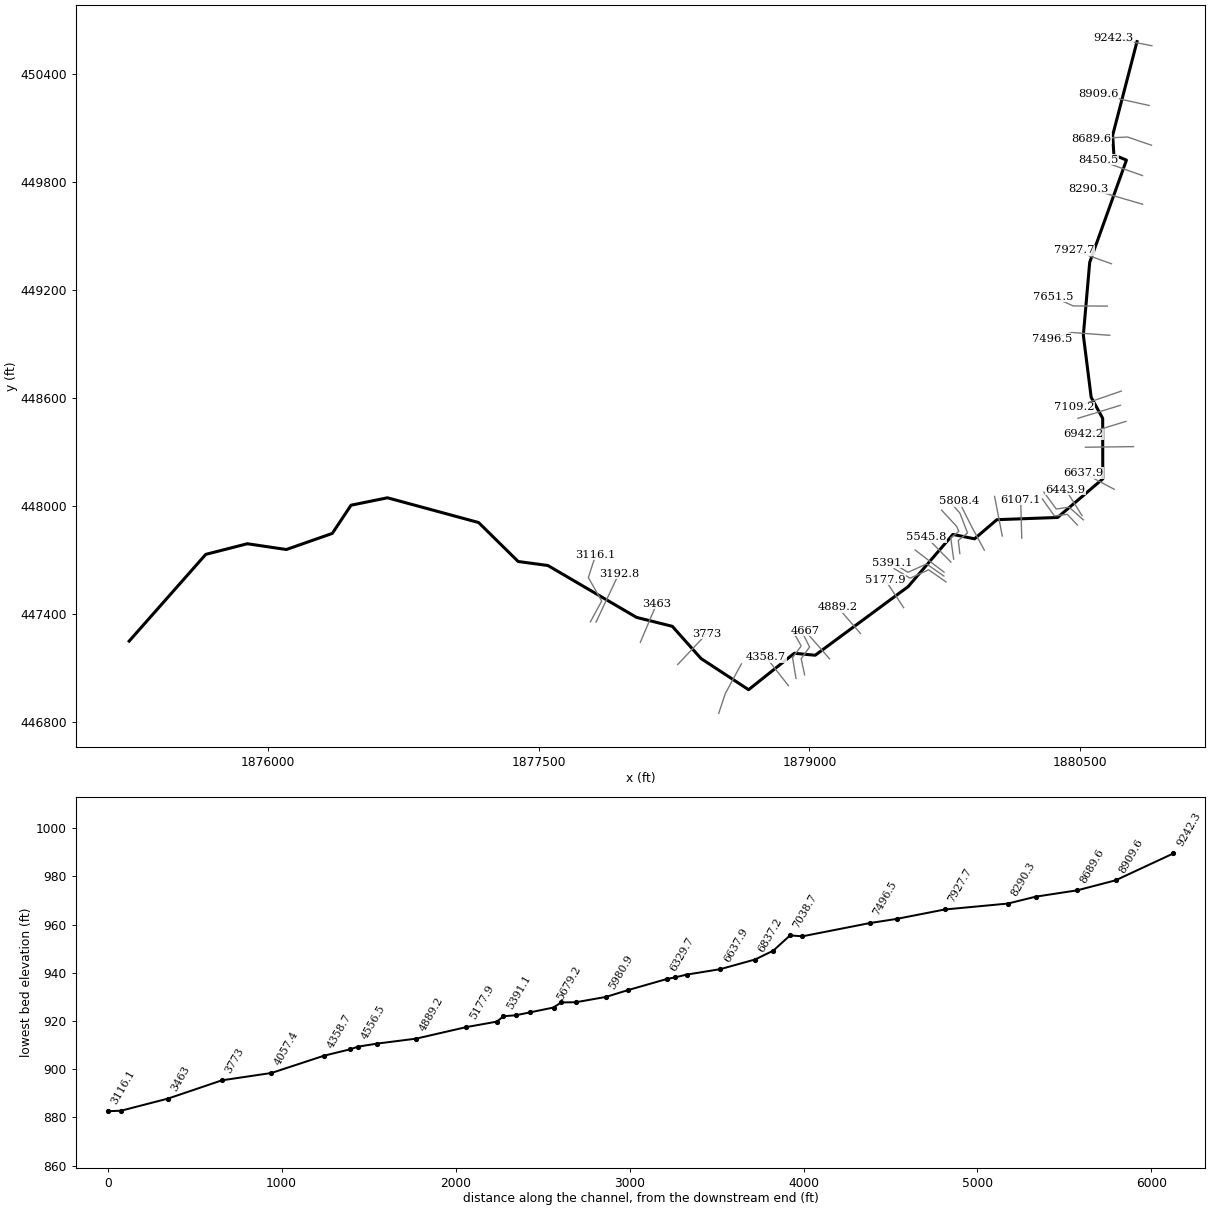
--- NP3.prj (project) ---

Proj Title=NP3
Current Plan=p01
Default Exp/Contr=0,0
English Units
Geom File=g01
Flow File=f01
Plan File=p01
BEGIN DESCRIPTION:
Cross-section geometry burned with contour data between RS 7038.7 and 7927.7 due to poor DEM quality.
END DESCRIPTION:
DSS Export Rating Curves= 0
DSS Export Rating Curve Sorted= 0
DSS Export Volume Flow Curves= 0
DXF OffsetX= 0
DXF OffsetY= 0
DXF ScaleX= 0
DXF ScaleY= 0

--- NP3.p01 (plan) ---

Plan Title=Floodplain
Program Version=4.00
Geom File=g01
Flow File=f01
K Sum by GR=0
Std Step Tol=0.01
Critical Tol=0.01
Num of Std Step Trials=20
Max Error Tol=0.3
Flow Tol Ratio=0.001
Split Flow NTrial=30
Split Flow Tol=0.02
Split Flow Ratio=0.02
Log Output Level=0
Friction Slope Method=1
Unsteady Friction Slope Method=2
Unsteady Bridges Friction Slope Method=1
Global Log Level=0
CheckData=False
Run HTab=0
Run UNet=0
Run PostProcess=0
UNET Theta=0
UNET Theta Warmup=0
UNET ZTol=0
UNET ZSATol=0
UNET MxIter=0
UNET MaxInSteps=0
UNET DtIC=0
UNET DtMin=0
UNET MaxCRTS=0
UNET WFStab=0
UNET SFStab=0
UNET WFX=0
UNET SFX=0
UNET DSS MLevel=0
UNET DZMax Abort=0
UNET Convert EG Bridges=0
UNET Use Existing IB Tables=0
UNET Froude Limit=0
UNET Froude Power=0
Write IC File=0
Echo Input=False
Echo Output=False
Write Detailed=0

--- NP3.f01 (steady flow) ---

Flow Title=NFF Regression Equation
Program Version=4.10
Number of Profiles= 1
Profile Names=P100yr
River Rch & RM=NP3,Main            ,9242.3
887.9021
River Rch & RM=NP3,Main            ,7927.7
911.3864
River Rch & RM=NP3,Main            ,6443.9
1005.705
River Rch & RM=NP3,Main            ,2834.3
1110.357
River Rch & RM=NP3,Main            ,577.4
1233.185
Boundary for River Rch & Prof#=NP3,Main            , 1
Up Type= 0
Dn Type= 3
Dn Slope=0.013
DSS Import GetInterval= 0
DSS Import GetPeak= 0
DSS Import FillOption= 0

--- NP3.g01 (geometry) ---

Geom Title=USGS 10m DEM
Program Version=4.10

River Reach=NP3             ,Main
Reach XY= 30
      1880815.46      450577.461     1880680.608       450057.28
     1880687.413      449948.222     1880756.976      449919.313
      1880553.33      449351.605     1880518.098      448946.423
     1880561.525      448601.588     1880625.308      448485.131
     1880625.814       448148.68     1880375.465      447934.359
     1880038.847      447922.016     1879914.939      447815.824
     1879794.975       447840.05     1879546.559      447549.811
     1879031.694      447169.042     1878915.828      447179.973
      1878662.53      446977.587     1878398.527      447150.975
     1878239.621      447329.711     1878041.443      447379.277
     1877550.076      447667.483     1877385.182      447689.771
     1877166.009      447906.186     1876660.512      448043.629
     1876458.689      448002.396     1876354.956      447845.712
     1876100.182      447756.302     1875884.048      447788.392
     1875653.676      447729.388      1875228.85      447247.484

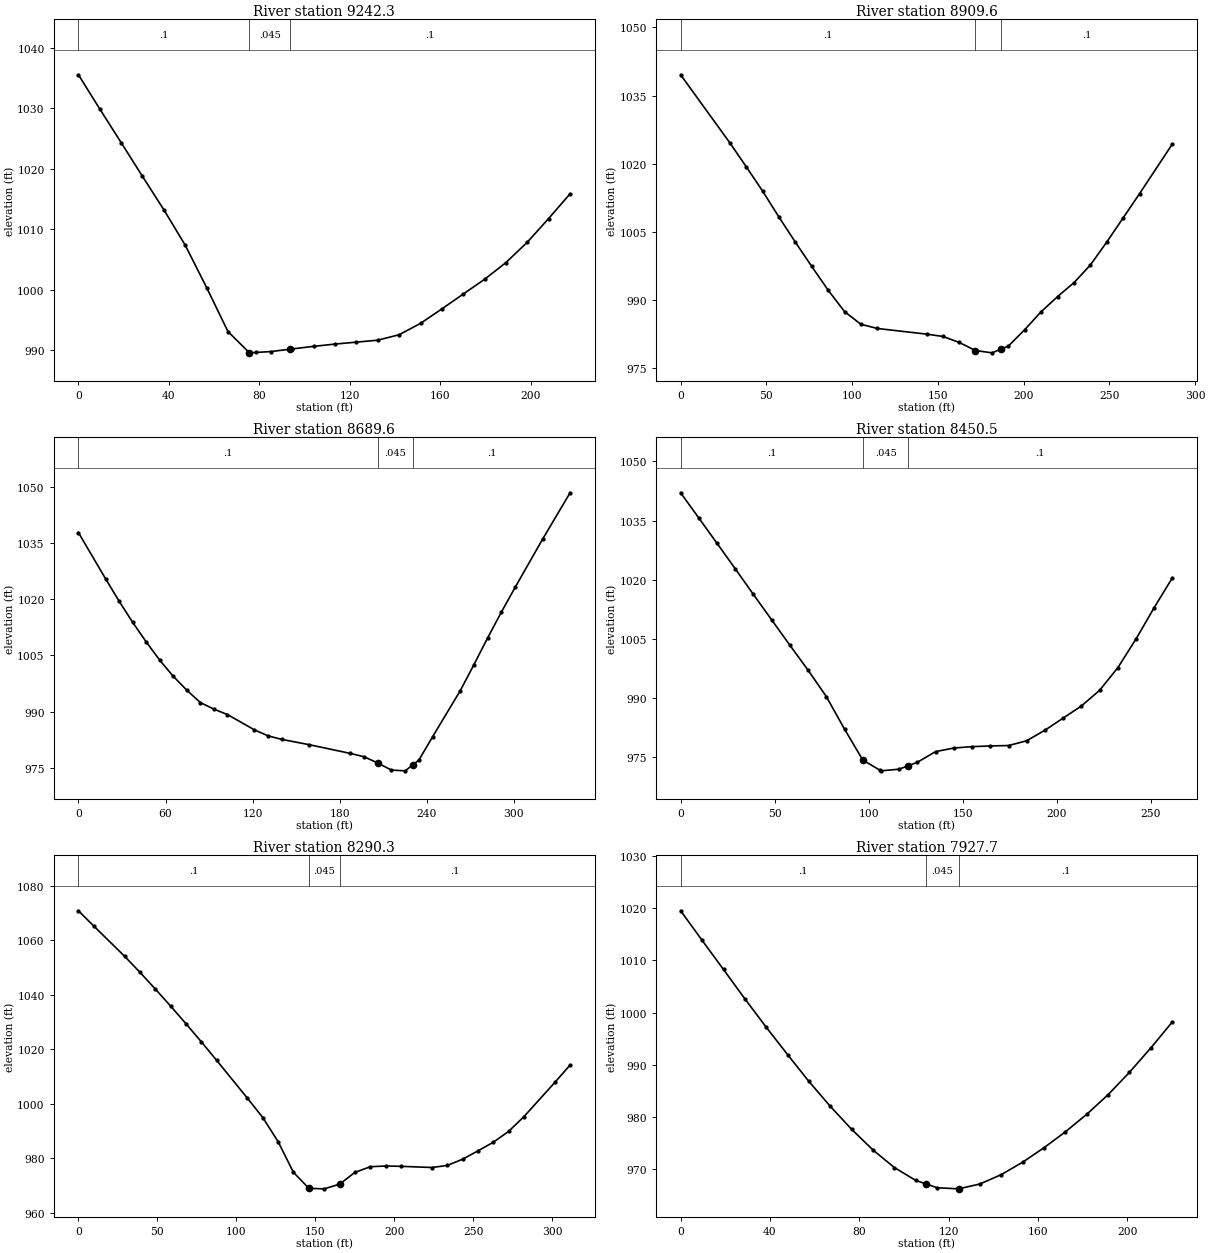
Type RM Length L Ch R = 1 ,9242.3  ,333.2,332.7,332
XS GIS Cut Line= 2
     1880898.299      450554.533     1880684.962      450595.713
#Sta/Elev= 26
       0 1035.56     9.4 1029.92    18.9 1024.33    28.3 1018.75    37.8  1013.2
    47.2 1007.36    56.7 1000.32    66.1  993.06    75.6  989.55    78.3  989.61
      85  989.76    93.3  990.14    94.5   990.2   103.9  990.62   113.4     991
   122.8  991.32   132.2  991.64   141.7  992.54   151.2  994.43   160.6  996.81
     170  999.26   179.5 1001.72   188.9 1004.47   198.4 1007.86   207.8 1011.77
   217.3 1015.87
#Mann= 3 , 0 , 0
       0      .1       0    75.6    .045       0    93.3      .1       0
Bank Sta=75.6,93.3
XS Rating Curve= 0 ,0
Exp/Cntr=0.3,0.1

Type RM Length L Ch R = 1 ,8909.6  ,214,220,225.8
XS GIS Cut Line= 2
     1880882.638      450222.906      1880602.69      450284.754
#Sta/Elev= 27
       0 1039.58    28.7  1024.6    38.2 1019.37    47.8 1013.98    57.3 1008.28
    66.9 1002.74    76.4  997.42      86  992.18    95.6  987.45   105.1  984.67
   114.7  983.74   143.4   982.5   152.9  981.99   162.5  980.66   171.9  978.89
   181.6  978.38   186.9  979.21   191.1  979.87   200.7   983.5   210.2  987.42
   219.8  990.76   229.4  993.84   238.9   997.7   248.5 1002.77     258 1008.06
   267.6 1013.41   286.7 1024.32
#Mann= 3 , 0 , 0
       0      .1       0   171.9    .045       0   186.9      .1       0
Bank Sta=171.9,186.9
XS Rating Curve= 0 ,0
Exp/Cntr=0.3,0.1

Type RM Length L Ch R = 1 ,8689.6  ,246.7,239.1,225.3
XS GIS Cut Line= 3
     1880895.901      450001.916     1880763.522      450047.489
     1880564.955      450038.809
#Sta/Elev= 30
       0 1037.75    18.7 1025.44      28 1019.48    37.3 1013.87    46.7 1008.61
      56 1003.74    65.3  999.46    74.7  995.73      84  992.44    93.3   990.7
   102.7  989.24   121.3  985.16   130.7  983.56     140  982.63   158.9  981.22
   187.3  978.89   196.8     978   206.3  976.32   215.7  974.44   225.2  974.24
   230.4  975.83   234.6  977.11   244.1  983.35     263  995.54   272.5 1002.52
     282 1009.69   291.4 1016.52   300.9 1023.13   319.8 1035.97   338.8 1048.36
#Mann= 3 , 0 , 0
       0      .1       0   206.3    .045       0   230.4      .1       0
Bank Sta=206.3,230.4
XS Rating Curve= 0 ,0
Exp/Cntr=0.3,0.1

Type RM Length L Ch R = 1 ,8450.5  ,158.8,160.3,161.5
XS GIS Cut Line= 2
     1880845.746      449833.366     1880599.435      449921.256
#Sta/Elev= 30
       0 1042.06     9.7 1035.65    19.4 1029.23    29.1 1022.77    38.7  1016.3
    48.4 1009.87    58.1 1003.44    67.8  997.09    77.5  990.42    87.2  982.14
    96.9  974.33   106.1  971.74   106.6   971.6   116.2  972.02   121.1   972.9
   125.9  973.77   135.6  976.47   145.3  977.38     155  977.73   164.7  977.91
   174.4  978.01     184  979.21   193.7  981.88   203.4  984.95   213.1  988.02
   222.8  991.98   232.5  997.72   242.2 1005.01   251.8  1012.9   261.5 1020.48
#Mann= 3 , 0 , 0
       0      .1       0    96.9    .045       0   121.1      .1       0
Bank Sta=96.9,121.1
XS Rating Curve= 0 ,0
Exp/Cntr=0.3,0.1

Type RM Length L Ch R = 1 ,8290.3  ,363.8,362.5,361.3
XS GIS Cut Line= 2
      1880846.71      449674.262     1880547.975      449761.393
#Sta/Elev= 29
       0  1070.9     9.7  1065.3    29.2  1054.2    38.9 1048.32    48.6  1042.2
    58.4 1035.85    68.1 1029.38    77.8 1022.75    87.5 1015.93     107 1002.01
   116.7  994.91   126.4  986.06   136.1  974.79   145.9  968.91   155.6  968.74
   165.3  970.46     175  974.79   184.8  976.87   194.5  977.13   204.2  977.01
   223.7  976.58   233.4  977.33   243.1   979.6   252.8  982.66   262.6  985.86
   272.3  989.86     282  995.28   301.5 1007.81   311.2 1014.22
#Mann= 3 , 0 , 0
       0      .1       0   145.9    .045       0   165.3      .1       0
Bank Sta=145.9,165.3
XS Rating Curve= 0 ,0
Exp/Cntr=0.3,0.1

Type RM Length L Ch R = 1 ,7927.7  ,268.6,276.2,283.8
XS GIS Cut Line= 2
     1880673.747      449343.708     1880466.282      449417.492
#Sta/Elev= 26
       0 1019.46     9.6 1013.82    19.2 1008.23    28.7 1002.66    38.3  997.21
    47.9  991.95    57.4  986.85      67  982.07    76.6  977.66    86.2  973.69
    95.7  970.36   105.3  967.89   109.7  967.25   114.9  966.49   124.5  966.28
   124.7   966.3     134   967.2   143.6     969   153.2  971.38   162.8  974.16
   172.3  977.18   181.9  980.54   191.5  984.31     201  988.56   210.6  993.23
   220.2   998.2
#Mann= 3 , 0 , 0
       0      .1       0   109.7    .045       0   124.7      .1       0
Bank Sta=109.7,124.7
XS Rating Curve= 0 ,0
Exp/Cntr=0.3,0.1

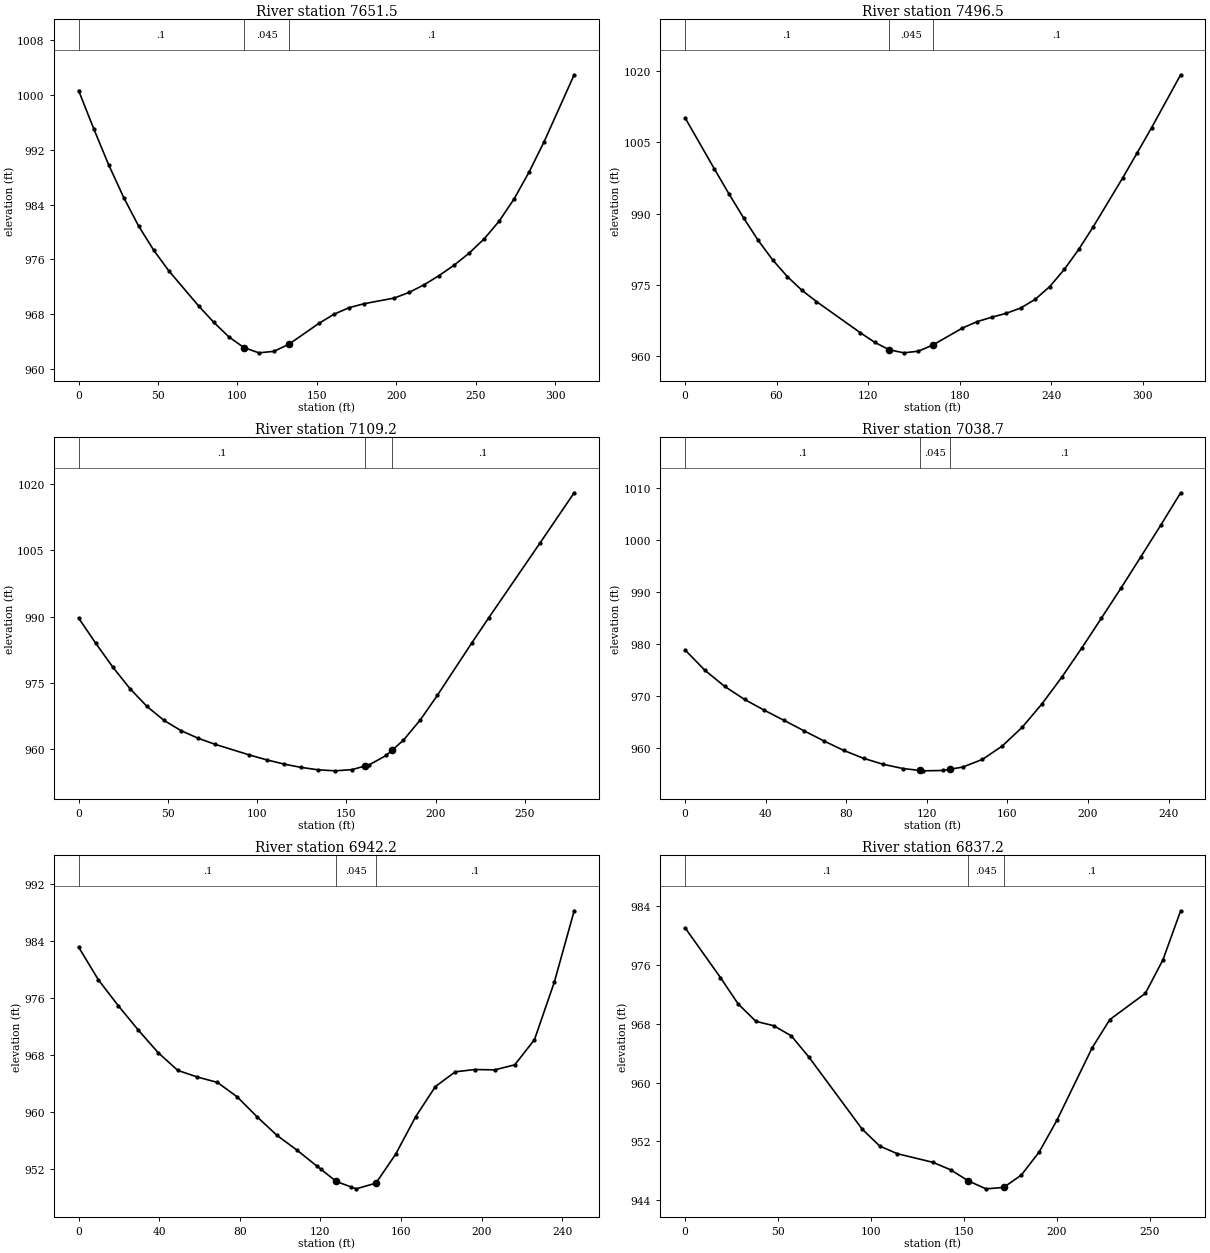
Type RM Length L Ch R = 1 ,7651.5  ,156.6,155,153.5
XS GIS Cut Line= 3
     1880651.178      449108.465     1880461.942      449109.333
     1880349.963       449159.68
#Sta/Elev= 30
       0 1000.63     9.5  995.07    18.9  989.81    28.4  985.03    37.8  980.86
    47.3  977.34    56.8  974.34    75.7  969.18    85.2  966.81    94.6  964.71
   104.1  963.14   113.5  962.38     123   962.6   132.5  963.65   151.4   966.7
   160.8  968.01   170.3  968.97   179.8  969.55   198.7  970.37   208.1   971.2
   217.6  972.32     227  973.66   236.5  975.18   245.9  976.93   255.4  979.02
   264.8   981.6   274.2  984.84   283.7  988.79   293.1  993.19     312 1002.94
#Mann= 3 , 0 , 0
       0      .1       0   104.1    .045       0   132.5      .1       0
Bank Sta=104.1,132.5
XS Rating Curve= 0 ,0
Exp/Cntr=0.3,0.1

Type RM Length L Ch R = 1 ,7496.5  ,378,387.3,396.5
XS GIS Cut Line= 3
     1880664.462       448946.12     1880454.602      448961.814
     1880345.227       448927.96
#Sta/Elev= 29
       0 1010.19    19.1  999.47    28.7  994.19    38.3  989.12    47.8  984.41
    57.4  980.24      67  976.73    76.5  973.86    86.1  971.46   114.8   964.9
   124.4  962.84   133.9  961.28   143.5  960.64     153  960.99   162.6  962.32
   181.8  965.86   191.3   967.2   200.9  968.14   210.4  968.96     220  970.08
   229.5  971.91   239.1  974.62   248.6  978.22   258.2   982.5   267.7  987.27
   286.8  997.47   296.3 1002.75   305.9 1008.14   324.9 1019.27
#Mann= 3 , 0 , 0
       0      .1       0   133.9    .045       0   162.6      .1       0
Bank Sta=133.9,162.6
XS Rating Curve= 0 ,0
Exp/Cntr=0.3,0.1

Type RM Length L Ch R = 1 ,7109.2  ,71.7,70.6,69.5
XS GIS Cut Line= 2
     1880728.742       448636.37     1880466.341       448545.74
#Sta/Elev= 27
       0  989.65     9.6  983.95    19.2  978.55    28.7  973.74    38.3  969.69
    47.9  966.52    57.4  964.22      67   962.5    76.6  961.12    95.7  958.73
   105.3  957.64   114.9  956.69   124.4  955.94     134  955.39   143.6  955.15
   153.2  955.43   160.6  956.26   162.7  956.49   172.3  958.63   175.6  959.81
   181.9  962.05   191.5  966.71     201  972.22   220.2  984.01   229.8  989.74
   258.5 1006.62   277.6 1017.94
#Mann= 3 , 0 , 0
       0      .1       0   160.6    .045       0   175.6      .1       0
Bank Sta=160.6,175.6
XS Rating Curve= 0 ,0
Exp/Cntr=0.3,0.1

Type RM Length L Ch R = 1 ,7038.7  ,96.1,96.4,96.7
XS GIS Cut Line= 2
     1880723.563      448557.375     1880488.386      448485.193
#Sta/Elev= 28
       0  978.82     9.8  974.92    19.7  971.79    29.5   969.3    39.4   967.2
    49.2  965.24      59  963.26    68.9   961.3    78.7  959.48    88.6  957.95
    98.4  956.79   108.2  955.98   116.4  955.62   118.1  955.54   127.9  955.61
   131.4  955.84   137.8  956.26   147.6  957.74   157.4  960.31   167.3  963.91
   177.1  968.41     187  973.57   196.8  979.13   206.6  984.91   216.5   990.8
   226.3   996.8   236.2  1002.9     246  1009.1
#Mann= 3 , 0 , 0
       0      .1       0   116.4    .045       0   131.4      .1       0
Bank Sta=116.4,131.4
XS Rating Curve= 0 ,0
Exp/Cntr=0.3,0.1

Type RM Length L Ch R = 1 ,6942.2  ,111.5,105,98.6
XS GIS Cut Line= 2
     1880754.232      448468.049     1880519.056      448395.867
#Sta/Elev= 28
       0  983.17     9.8  978.58    19.7  974.93    29.5  971.56    39.4  968.36
    49.2  965.85      59  964.91    68.9  964.16    78.7  962.13    88.6  959.32
    98.4  956.73   108.2  954.68   118.1  952.44   120.1  951.99   127.9  950.24
   135.1  949.48   137.8   949.2   147.6     950   157.4  954.08   167.3  959.33
   177.1  963.58     187  965.65   196.8  965.97   206.6  965.92   216.5  966.63
   226.3  970.17   236.2   978.3     246  988.28
#Mann= 3 , 0 , 0
       0      .1       0   127.9    .045       0   147.6      .1       0
Bank Sta=127.9,147.6
XS Rating Curve= 0 ,0
Exp/Cntr=0.3,0.1

Type RM Length L Ch R = 1 ,6837.2  ,210.5,199.4,187.8
XS GIS Cut Line= 2
     1880796.289      448327.879     1880529.796      448324.406
#Sta/Elev= 23
       0  981.08      19  974.31    28.6  970.69    38.1  968.34    47.6  967.75
    57.1  966.37    66.6  963.47    95.2  953.67   104.7  951.35   114.2  950.31
   133.3  949.14   142.8  948.12   152.4   946.6   161.8  945.53   171.3  945.72
   180.8   947.4   190.4  950.54   199.9  954.84   218.9  964.73   228.4  968.58
   247.5  972.15     257  976.73   266.5   983.4
#Mann= 3 , 0 , 0
       0      .1       0   152.4    .045       0   171.3      .1       0
Bank Sta=152.4,171.3
XS Rating Curve= 0 ,0
Exp/Cntr=0.3,0.1

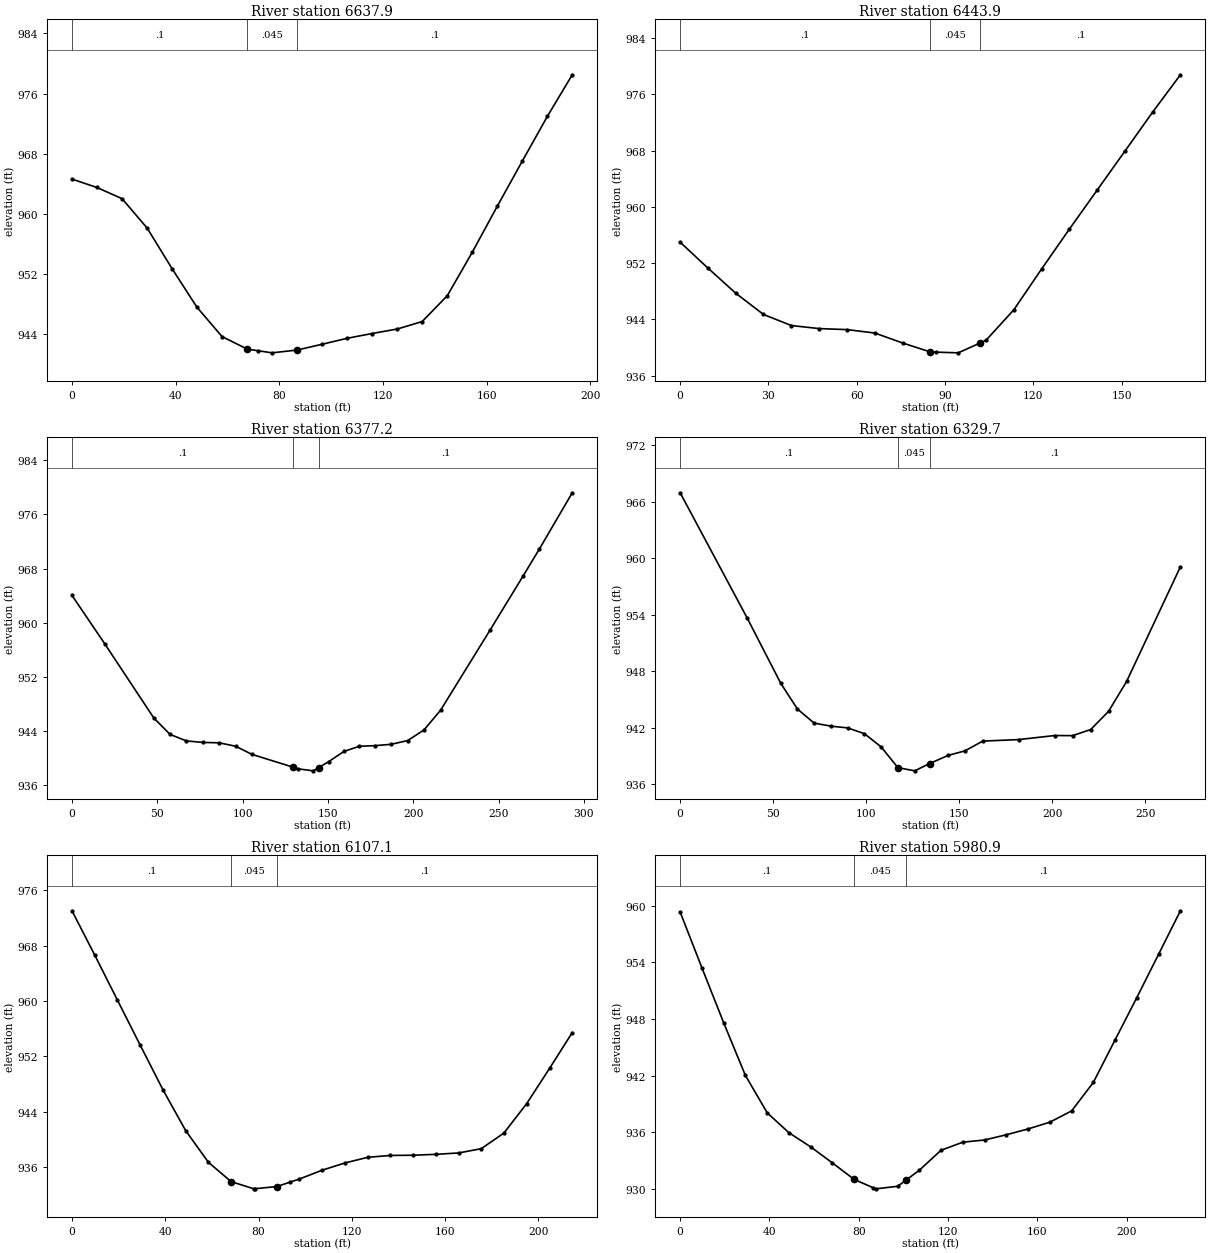
Type RM Length L Ch R = 1 ,6637.9  ,205.6,194,181.9
XS GIS Cut Line= 2
     1880689.637       448090.78     1880519.204      448181.359
#Sta/Elev= 22
       0  964.64     9.6  963.52    19.3  962.04      29  958.12    38.6  952.73
    48.2   947.6    57.9  943.69    67.6  942.03    71.8  941.81    77.2  941.53
    86.8   941.9    96.5  942.67   106.2  943.47   115.8   944.1   125.5   944.7
   135.1  945.69   144.8  949.13   154.4  954.89   164.1  961.04   173.7  967.01
   183.4  972.98     193  978.51
#Mann= 3 , 0 , 0
       0      .1       0    67.6    .045       0    86.8      .1       0
Bank Sta=67.6,86.8
XS Rating Curve= 0 ,0
Exp/Cntr=0.3,0.1

Type RM Length L Ch R = 1 ,6443.9  ,35.5,66.7,95.1
XS GIS Cut Line= 2
     1880510.815      447944.576     1880420.538      448088.673
#Sta/Elev= 21
       0  954.99     9.4  951.32    18.9  947.73    28.3  944.72    37.8  943.14
    47.2  942.71    56.7  942.56    66.1  942.08    75.6  940.66      85  939.39
      87  939.36    94.5  939.26     102  940.67   103.9  941.03   113.4  945.38
   122.8  951.16   132.2   956.8   141.7  962.38   151.2  967.96   160.6  973.49
     170  978.78
#Mann= 3 , 0 , 0
       0      .1       0      85    .045       0     102      .1       0
Bank Sta=85,102
XS Rating Curve= 0 ,0
Exp/Cntr=0.3,0.1

Type RM Length L Ch R = 1 ,6377.2  ,49,47.5,44.2
XS GIS Cut Line= 4
      1880517.76      447921.138     1880439.101      447991.366
      1880367.87      447981.508     1880299.397      448074.974
#Sta/Elev= 25
       0  964.03    19.2  956.88    47.9  945.93    57.5  943.48    67.1  942.52
    76.7   942.3    86.3  942.24    95.9  941.74   105.4  940.54   129.6  938.64
   132.4   938.4   141.4   938.1   144.6  938.58   150.4  939.45   159.4  940.97
   168.4  941.73   177.4  941.82     187  942.02   196.7  942.57   206.3  944.14
     216  947.05   244.9  958.85   264.3  966.86   273.9  970.87   293.2   979.2
#Mann= 3 , 0 , 0
       0      .1       0   129.6    .045       0   144.6      .1       0
Bank Sta=129.6,144.6
XS Rating Curve= 0 ,0
Exp/Cntr=0.3,0.1

Type RM Length L Ch R = 1 ,6329.7  ,263.9,222.6,184.8
XS GIS Cut Line= 4
     1880484.774      447892.493     1880429.376      447951.658
     1880358.021      447942.741     1880290.788      448037.103
#Sta/Elev= 22
       0  966.97      36  953.67      54  946.75      63     944      72   942.5
      81  942.18      90  941.99      99  941.38     108  939.97     117  937.77
     126  937.43     134   938.2     144  939.07     153  939.55   162.6  940.59
   181.9  940.75   201.2  941.18   210.9  941.17   220.6  941.82   230.2  943.75
   239.9  946.93   268.8  959.11
#Mann= 3 , 0 , 0
       0      .1       0     117    .045       0     134      .1       0
Bank Sta=117,134
XS Rating Curve= 0 ,0
Exp/Cntr=0.3,0.1

Type RM Length L Ch R = 1 ,6107.1  ,122,126.2,129.5
XS GIS Cut Line= 2
     1880176.614      447819.576     1880170.538      448033.986
#Sta/Elev= 25
       0  973.05     9.8  966.61    19.5  960.12    29.2  953.65      39  947.16
    48.8  941.22    58.5  936.67    68.2  933.88      78  932.83    78.5  932.85
    87.8  933.16    93.5   933.8    97.5  934.25   107.2  935.52     117  936.57
   126.8  937.39   136.5  937.66   146.2  937.69     156  937.82   165.8  938.02
   175.5  938.64   185.2   940.9     195  945.17   204.8  950.27   214.5  955.43
#Mann= 3 , 0 , 0
       0      .1       0    68.2    .045       0    87.8      .1       0
Bank Sta=68.2,87.8
XS Rating Curve= 0 ,0
Exp/Cntr=0.3,0.1

Type RM Length L Ch R = 1 ,5980.9  ,166.8,172.5,176.6
XS GIS Cut Line= 2
     1880068.756      447831.407      1880026.05      448051.248
#Sta/Elev= 26
       0  959.32     9.7  953.44    19.5  947.59    29.2  942.03      39  938.06
    48.7  935.96    58.4  934.47    68.2  932.76    77.9  931.02    86.3  930.15
    87.6  930.02    97.4  930.29   101.3  930.97   107.1  931.99   116.8   934.1
   126.6  934.96   136.3  935.19     146  935.74   155.8  936.36   165.5  937.07
   175.3  938.27     185  941.28   194.7  945.76   204.5  950.27   214.2  954.83
     224  959.45
#Mann= 3 , 0 , 0
       0      .1       0    77.9    .045       0   101.3      .1       0
Bank Sta=77.9,101.3
XS Rating Curve= 0 ,0
Exp/Cntr=0.3,0.1

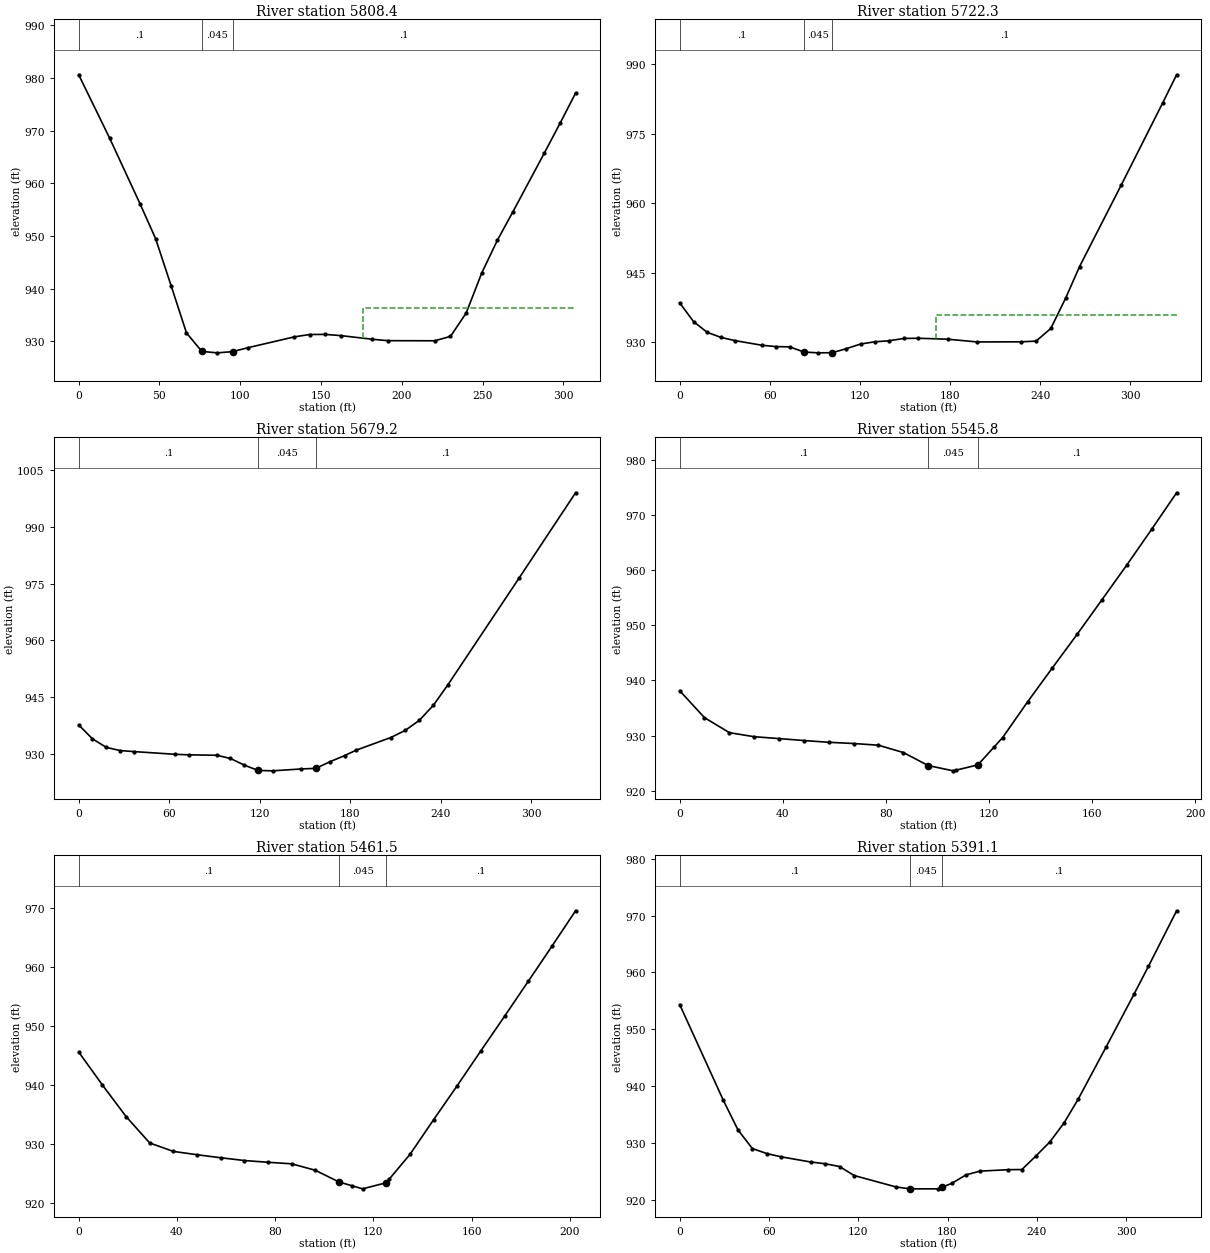
Type RM Length L Ch R = 1 ,5808.4  ,117.8,86.1,55.9
XS GIS Cut Line= 3
     1879969.422      447752.681     1879901.412      447878.395
     1879827.632      448025.542
#Sta/Elev= 25
       0   980.6    19.1   968.6    38.1  956.01    47.6  949.49    57.2  940.55
    66.7   931.6    76.2  928.08    85.8  927.81    95.3  928.04   104.8  928.79
   133.4  930.84   142.9  931.29   152.6  931.31   162.3  931.08   181.7  930.39
   191.4  930.12   220.4   930.1   230.1  930.94   239.8  935.36   249.4  942.94
   259.1  949.18   268.8  954.63   288.2  965.75   297.9  971.39   307.5  977.11
#Mann= 3 , 0 , 0
       0      .1       0    76.2    .045       0    95.3      .1       0
#XS Ineff= 2 , 0
                          175.66          936.34
Permanent Ineff=
       F       F
Bank Sta=76.2,95.3
XS Rating Curve= 0 ,0
Exp/Cntr=0.3,0.1

Type RM Length L Ch R = 1 ,5722.3  ,54.1,43.1,51.1
XS GIS Cut Line= 5
     1879833.522       447733.91     1879824.861      447806.626
     1879876.076      447848.292     1879833.974      447958.164
      1879785.59      448014.001
#Sta/Elev= 27
       0  938.49     9.2  934.46    18.3  932.14    27.5  931.05    36.6  930.37
    54.9  929.35    64.1  929.07    73.2  929.01    82.7  927.89    92.1  927.72
   101.5  927.75     111  928.63   120.4  929.62   129.8   930.1   139.2  930.32
   149.1  930.82   158.9  930.87   178.5  930.66   198.1  930.07   227.5   930.1
   237.3  930.26   247.1  933.01   256.9  939.51   266.2  946.35   293.9  963.91
   321.6  981.71   330.8  987.74
#Mann= 3 , 0 , 0
       0      .1       0    82.7    .045       0   101.5      .1       0
#XS Ineff= 2 , 0
                          170.37          935.89
Permanent Ineff=
       F       F
Bank Sta=82.7,101.5
XS Rating Curve= 0 ,0
Exp/Cntr=0.3,0.1

Type RM Length L Ch R = 1 ,5679.2  ,83.6,133.4,163.6
XS GIS Cut Line= 5
     1879799.192      447702.807     1879783.033      447820.584
     1879827.646      447856.879     1879815.679       447884.99
      1879732.42      447974.844
#Sta/Elev= 24
       0  937.73     9.1  934.06    18.3   931.8    27.4  930.96    36.6  930.69
      64  929.97    73.2  929.83    91.4  929.72   100.6  928.88   109.7  927.13
   118.9  925.72   128.5  925.61   147.6  926.11   157.2  926.26   166.8  928.05
   176.4  929.65     184  931.07   206.9   934.4   216.4  936.26   225.8  938.92
   235.2  942.94   244.6  948.21   291.8  976.37   329.4  998.97
#Mann= 3 , 0 , 0
       0      .1       0   118.9    .045       0   157.2      .1       0
Bank Sta=118.9,157.2
XS Rating Curve= 0 ,0
Exp/Cntr=0.3,0.1

Type RM Length L Ch R = 1 ,5545.8  ,81.1,84.3,87.5
XS GIS Cut Line= 2
     1879783.968      447686.575     1879648.966      447824.263
#Sta/Elev= 23
       0  938.13     9.6  933.26    19.3  930.54    28.9  929.81    38.6  929.47
    48.2  929.12    57.8   928.8    67.5  928.58    77.1  928.27    86.8  926.94
    96.4  924.59   106.1  923.63   107.1  923.74   115.7  924.71   122.1  928.01
   125.3  929.66     135  936.14   144.6  942.28   154.3  948.42   163.9  954.66
   173.6  960.99   183.2  967.43   192.8  973.99
#Mann= 3 , 0 , 0
       0      .1       0    96.4    .045       0   115.7      .1       0
Bank Sta=96.4,115.7
XS Rating Curve= 0 ,0
Exp/Cntr=0.3,0.1

Type RM Length L Ch R = 1 ,5461.5  ,22.6,70.4,95.9
XS GIS Cut Line= 2
     1879745.966       447630.56     1879585.441      447753.659
#Sta/Elev= 24
       0  945.62     9.6  940.06    19.3  934.66    28.9  930.18    38.5  928.75
    48.2  928.18    57.8  927.67    67.4   927.2    77.1   926.9    86.7  926.64
    96.3  925.55     106  923.55   111.4   922.9   115.6  922.39   125.2  923.42
   126.4  924.02   134.9  928.25   144.5  934.13   154.1   939.9   163.8  945.86
   173.4   951.7     183  957.61   192.7   963.6   202.3  969.61
#Mann= 3 , 0 , 0
       0      .1       0     106    .045       0   125.2      .1       0
Bank Sta=106,125.2
XS Rating Curve= 0 ,0
Exp/Cntr=0.3,0.1

Type RM Length L Ch R = 1 ,5391.1  ,56.6,36.9,54.8
XS GIS Cut Line= 4
     1879745.064      447608.916      1879649.02      447676.102
     1879546.212      447629.658     1879456.931      447682.866
#Sta/Elev= 27
       0  954.35    29.3  937.55    39.1  932.37    48.8  929.08    58.6  928.19
    68.4  927.61    87.9  926.72    97.7  926.41   107.4  925.92   117.2  924.34
   145.4  922.33   154.8     922   173.6     922   176.3  922.28     183  922.98
   192.4  924.45   201.8  925.11   220.6  925.36     230  925.39   239.5  927.79
   248.9  930.27   258.4   933.6   267.8  937.73   286.7  946.96   305.6   956.3
   315.1  961.09     334  970.83
#Mann= 3 , 0 , 0
       0      .1       0   154.8    .045       0   176.3      .1       0
Bank Sta=154.8,176.3
XS Rating Curve= 0 ,0
Exp/Cntr=0.3,0.1

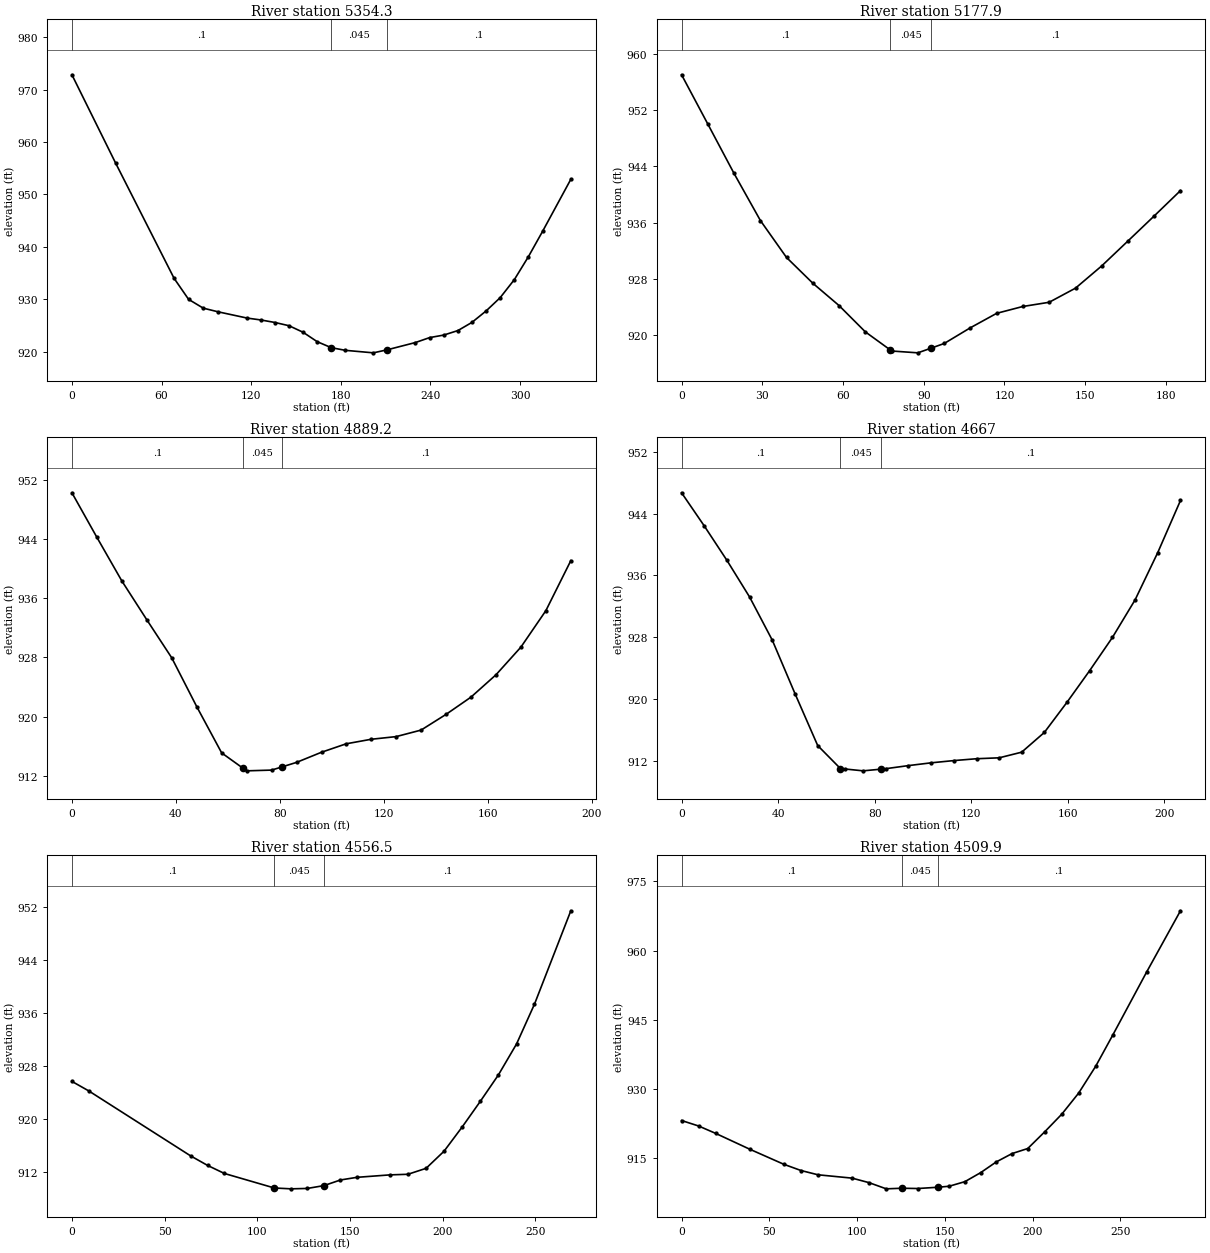
Type RM Length L Ch R = 1 ,5354.3  ,209.2,176.3,125.7
XS GIS Cut Line= 4
     1879756.788      447576.451     1879660.743      447643.636
     1879557.935      447597.193     1879468.655        447650.4
#Sta/Elev= 27
       0  972.84    29.3  955.96    68.4  933.99    78.1  929.98    87.9   928.3
    97.7  927.61   117.2  926.41   126.6  926.04     136  925.56   145.4  924.94
   154.8  923.69   164.2   921.9   173.6  920.76     183  920.25   201.8  919.77
   211.2  920.36     230  921.74   239.5  922.68   248.9  923.16   258.4  924.02
   267.8  925.58   277.3  927.77   286.7   930.3   296.2  933.75   305.6  938.12
   315.1  942.96     334  952.89
#Mann= 3 , 0 , 0
       0      .1       0   173.6    .045       0   211.2      .1       0
Bank Sta=173.6,211.2
XS Rating Curve= 0 ,0
Exp/Cntr=0.3,0.1

Type RM Length L Ch R = 1 ,5177.9  ,285.7,288.7,291.5
XS GIS Cut Line= 2
     1879522.227      447433.216     1879419.797       447587.73
#Sta/Elev= 22
       0  957.03     9.8  949.99    19.5     943    29.3   936.3      39  931.05
    48.8  927.38    58.5  924.22    68.3  920.47    77.6  917.89    78.1  917.75
    87.8  917.49    92.6  918.14    97.6  918.82   107.3  921.05   117.1  923.11
   126.8  924.08   136.6  924.68   146.4  926.69   156.1  929.84   165.9   933.4
   175.6  936.94   185.4  940.56
#Mann= 3 , 0 , 0
       0      .1       0    77.6    .045       0    92.6      .1       0
Bank Sta=77.6,92.6
XS Rating Curve= 0 ,0
Exp/Cntr=0.3,0.1

Type RM Length L Ch R = 1 ,4889.2  ,222.1,222.2,222.3
XS GIS Cut Line= 2
     1879282.245      447290.301     1879156.647      447435.378
#Sta/Elev= 23
       0  950.23     9.6  944.22    19.2  938.33    28.8  933.09    38.4  927.95
      48  921.37    57.6  915.12    65.7  913.08    67.2   912.7    76.8   912.8
    80.7  913.22    86.4  913.84      96  915.21   105.5  916.35   115.1  916.96
   124.7  917.32   134.3   918.2   143.9  920.32   153.5  922.65   163.1  925.66
   172.7   929.4   182.3  934.32   191.9  941.07
#Mann= 3 , 0 , 0
       0      .1       0    65.7    .045       0    80.7      .1       0
Bank Sta=65.7,80.7
XS Rating Curve= 0 ,0
Exp/Cntr=0.3,0.1

Type RM Length L Ch R = 1 ,4667    ,141.2,110.4,79.7
XS GIS Cut Line= 2
     1879111.068      447149.401      1878975.13       447305.13
#Sta/Elev= 25
       0  946.73     9.4  942.43    18.8  937.96    28.2   933.2    37.6   927.6
      47  920.67    56.4  913.94    65.8  910.96    67.7   910.9    75.2  910.66
    82.7  910.88    84.6  910.94      94  911.34   103.4   911.7   112.8  911.99
   122.2  912.23   131.6  912.35   140.9  913.08   150.3  915.64   159.7  919.56
   169.1  923.67   178.5  927.96   187.9  932.84   197.3  938.98   206.7  945.73
#Mann= 3 , 0 , 0
       0      .1       0    65.8    .045       0    82.7      .1       0
Bank Sta=65.8,82.7
XS Rating Curve= 0 ,0
Exp/Cntr=0.3,0.1

Type RM Length L Ch R = 1 ,4556.5  ,60.2,46.6,43
XS GIS Cut Line= 4
        1878973.      447060.182     1878953.943      447149.612
     1879000.621      447214.752     1878956.901      447302.005
#Sta/Elev= 21
       0  925.64     9.1   924.2      64  914.39    73.2  912.94    82.3  911.72
   109.2  909.53   118.2   909.4     127  909.46     136  909.89   144.9  910.74
   153.8  911.14   171.6  911.51   181.3   911.6   191.1   912.5   200.8  915.09
   210.6  918.76   220.4  922.64   230.1  926.61   239.9  931.29   249.6  937.32
   269.2  951.43
#Mann= 3 , 0 , 0
       0      .1       0   109.2    .045       0     136      .1       0
Bank Sta=109.2,136
XS Rating Curve= 0 ,0
Exp/Cntr=0.3,0.1

Type RM Length L Ch R = 1 ,4509.9  ,107.5,151.2,183.9
XS GIS Cut Line= 4
     1878925.231       447040.69      1878906.11      447155.692
     1878954.222      447220.423     1878911.589      447296.276
#Sta/Elev= 26
       0  923.11     9.7  921.92    19.4  920.32    38.9  916.87    58.3   913.6
      68  912.26    77.7  911.33    97.2   910.6   106.9  909.61   116.6  908.28
   125.5  908.41   134.5  908.35   145.8  908.62   152.4  908.84   161.4  909.84
   170.4   911.8   179.3  914.13   188.3  915.94   197.2  917.03   206.9  920.67
   216.6  924.49   226.2  929.06   235.9  934.88   245.6  941.63   264.9  955.32
   284.2  968.63
#Mann= 3 , 0 , 0
       0      .1       0   125.5    .045       0   145.8      .1       0
Bank Sta=125.5,145.8
XS Rating Curve= 0 ,0
Exp/Cntr=0.3,0.1

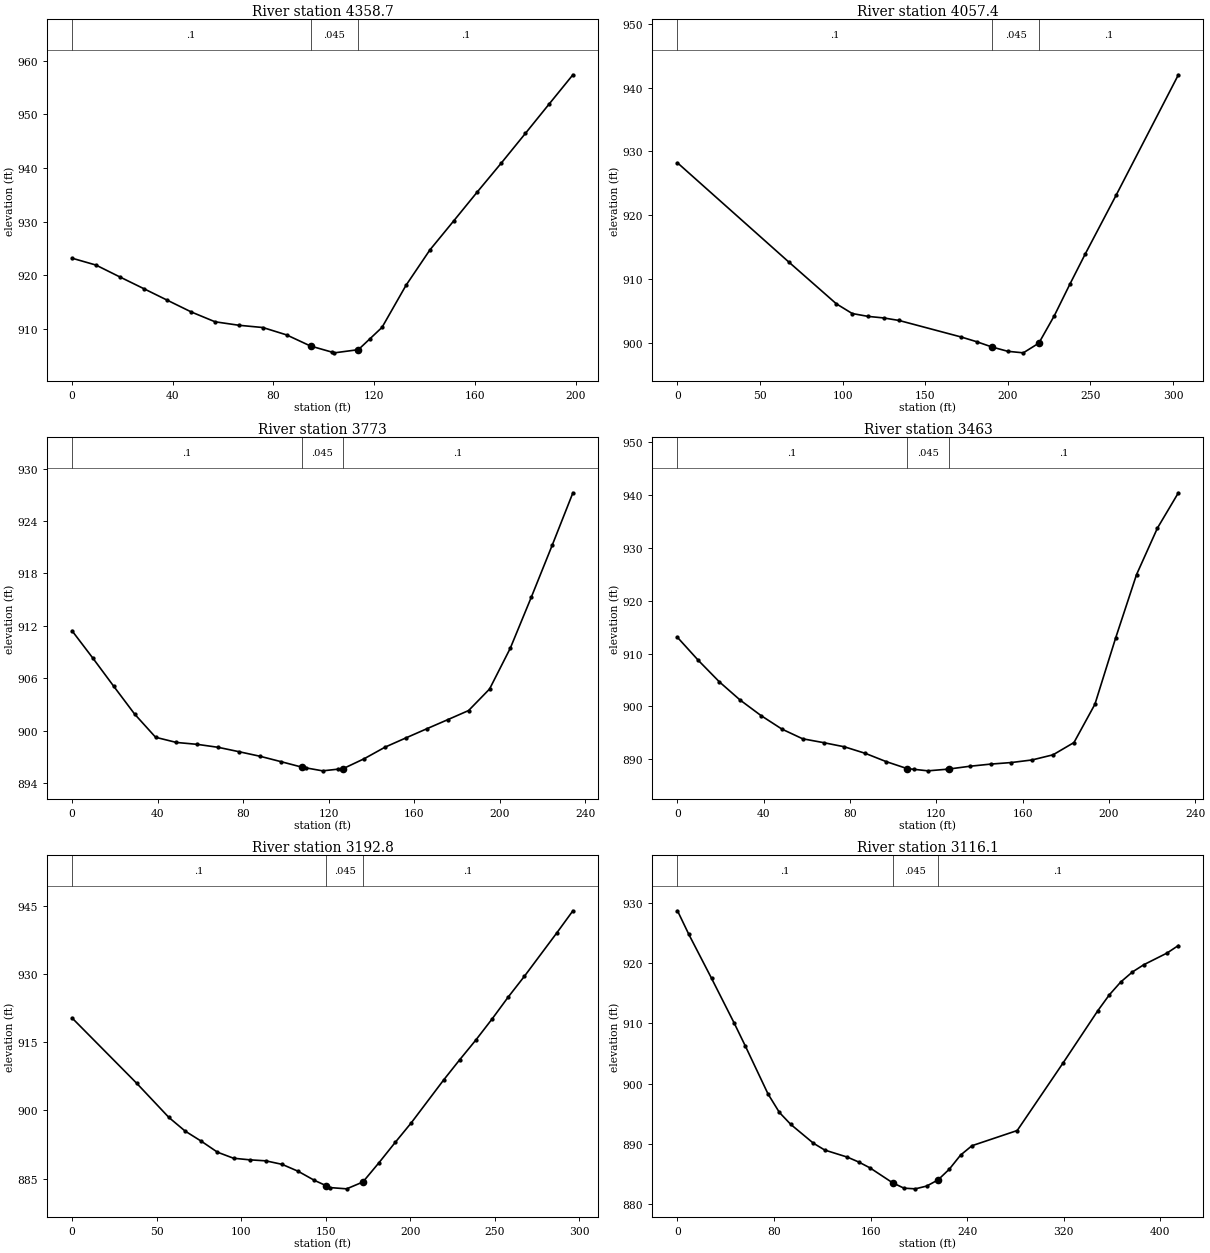
Type RM Length L Ch R = 1 ,4358.7  ,327.4,301.3,274.5
XS GIS Cut Line= 2
     1878883.382      447000.003     1878760.684      447156.568
#Sta/Elev= 24
       0  923.22     9.5  921.94    18.9  919.75    28.4  917.57    37.9  915.38
    47.4   913.2    56.8  911.38    66.3  910.73    75.8  910.31    85.2  908.94
    94.7  906.87   103.4  905.71   104.2   905.6   113.7  906.19   118.4  908.26
   123.1  910.34   132.6  918.15   142.1  924.75   151.6  930.18     161  935.59
   170.5  940.95     180  946.43   189.4  951.88   198.9  957.36
#Mann= 3 , 0 , 0
       0      .1       0    94.7    .045       0   113.7      .1       0
Bank Sta=94.7,113.7
XS Rating Curve= 0 ,0
Exp/Cntr=0.3,0.1

Type RM Length L Ch R = 1 ,4057.4  ,290.2,284.4,278.3
XS GIS Cut Line= 3
      1878496.84      446846.126     1878533.281      446955.675
     1878622.444      447121.006
#Sta/Elev= 18
       0  928.22    67.4  912.68    96.2  906.13   105.8  904.61   115.4  904.16
   124.8  903.92   134.2  903.52   171.8  900.93   181.2  900.19   190.6  899.35
     200  898.69   209.4  898.45   218.8  899.97   228.2  904.28   237.6  909.21
   246.9  913.94   265.7   923.2   303.3  942.02
#Mann= 3 , 0 , 0
       0      .1       0   190.6    .045       0   218.8      .1       0
Bank Sta=190.6,218.8
XS Rating Curve= 0 ,0
Exp/Cntr=0.3,0.1

Type RM Length L Ch R = 1 ,3773    ,301.2,310,318.5
XS GIS Cut Line= 2
     1878269.424      447117.322     1878429.841      447288.155
#Sta/Elev= 27
       0  911.44     9.8  908.29    19.5  905.09    29.3   901.9    39.1  899.25
    48.8  898.66    58.6  898.44    68.4   898.1    78.1   897.6    87.9  897.08
    97.6  896.47   107.4  895.84   109.4  895.75   117.2  895.41   124.4   895.6
   126.9  895.67   136.7   896.8   146.5  898.13   156.2  899.18     166  900.23
   175.8  901.27   185.5  902.31   195.3  904.77     205  909.44   214.8  915.26
   224.6  921.22   234.3  927.23
#Mann= 3 , 0 , 0
       0      .1       0   107.4    .045       0   126.9      .1       0
Bank Sta=107.4,126.9
XS Rating Curve= 0 ,0
Exp/Cntr=0.3,0.1

Type RM Length L Ch R = 1 ,3463    ,270.7,270.2,268.9
XS GIS Cut Line= 2
      1878062.48      447240.933     1878152.758      447454.822
#Sta/Elev= 27
       0  913.05     9.7  908.69    19.4  904.65      29  901.22    38.7  898.28
    48.4  895.72      58  893.89    67.7  893.16    77.4  892.37    87.1  891.13
    96.7  889.58   106.4  888.26   109.8  888.11   116.1  887.83   124.8  888.13
   125.8  888.17   135.4  888.69   145.1   889.1   154.8   889.4   164.4  889.89
   174.1  890.86   183.8  893.18   193.5  900.41   203.1  912.92   212.8  924.92
   222.5  933.72   232.2  940.38
#Mann= 3 , 0 , 0
       0      .1       0   106.4    .045       0   125.8      .1       0
Bank Sta=106.4,125.8
XS Rating Curve= 0 ,0
Exp/Cntr=0.3,0.1

Type RM Length L Ch R = 1 ,3192.8  ,45.9,76.8,107.3
XS GIS Cut Line= 2
     1877817.093      447353.597     1877943.227      447621.542
#Sta/Elev= 27
       0  920.32    38.2  905.99    57.3  898.46    66.9  895.47    76.4  893.26
      86  890.84    95.5  889.51   105.1  889.16   114.6  888.94   124.2  888.17
   133.7  886.65   143.3  884.66   150.4  883.46   152.8  883.06   162.4  882.79
     172  884.29   181.5  888.52   191.1  892.98   200.6  897.28   219.7  906.67
   229.3  911.16   238.8  915.47   248.4  920.09   257.9  924.89   267.5  929.46
   286.6  938.96   296.2  943.85
#Mann= 3 , 0 , 0
       0      .1       0   150.4    .045       0     172      .1       0
Bank Sta=150.4,172
XS Rating Curve= 0 ,0
Exp/Cntr=0.3,0.1

Type RM Length L Ch R = 1 ,3116.1  ,84.4,83.5,84.4
XS GIS Cut Line= 4
      1877785.59      447354.565     1877848.211       447470.02
     1877774.241      447600.604     1877815.439      447727.591
#Sta/Elev= 30
       0  928.69     9.4  924.77    28.2  917.49    46.9  910.09    56.3  906.22
      75  898.31    84.4  895.25    93.8  893.27   112.6  890.14     122  889.01
   140.7  887.84   150.1  887.03   159.5  886.05   178.2  883.58   187.6  882.69
     197  882.58   206.4  883.04   215.8  884.06   225.1  885.83   234.5  888.18
   243.9  889.73   281.4  892.25   319.6  903.52   348.2  912.13   357.7  914.75
   367.2  916.89   376.8  918.54   386.3  919.75   405.4  921.67   414.9  922.93
#Mann= 3 , 0 , 0
       0      .1       0   178.2    .045       0   215.8      .1       0
Bank Sta=178.2,215.8
XS Rating Curve= 0 ,0
Exp/Cntr=0.3,0.1