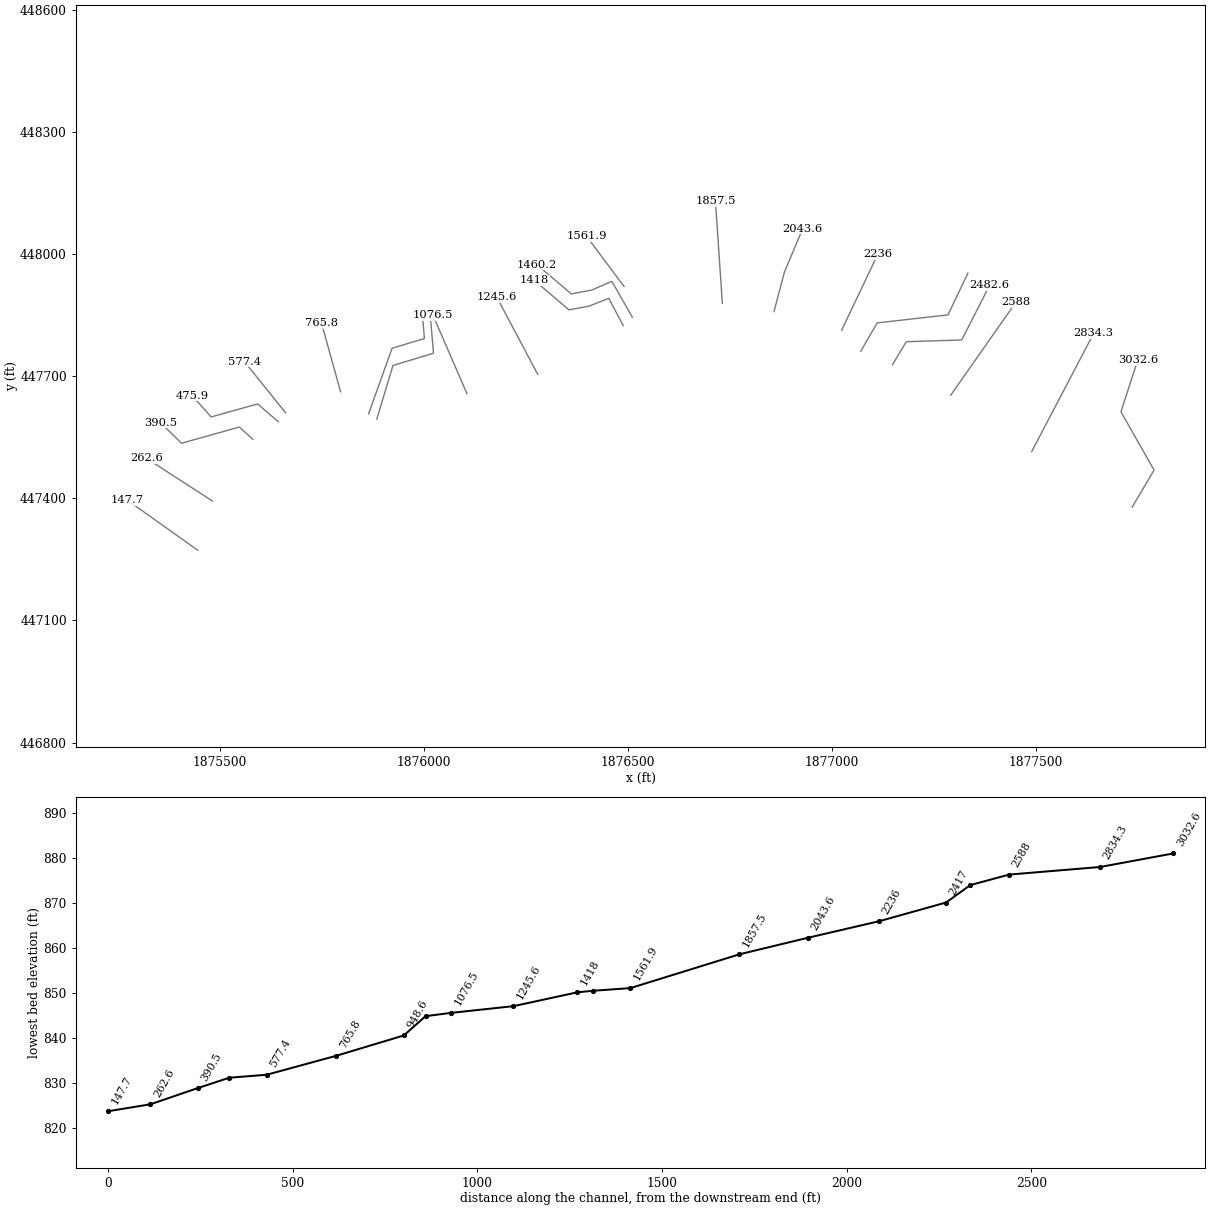
HEC-RAS study NP3.prj: NP3

--- NP3.g01 (geometry) --- (continued)

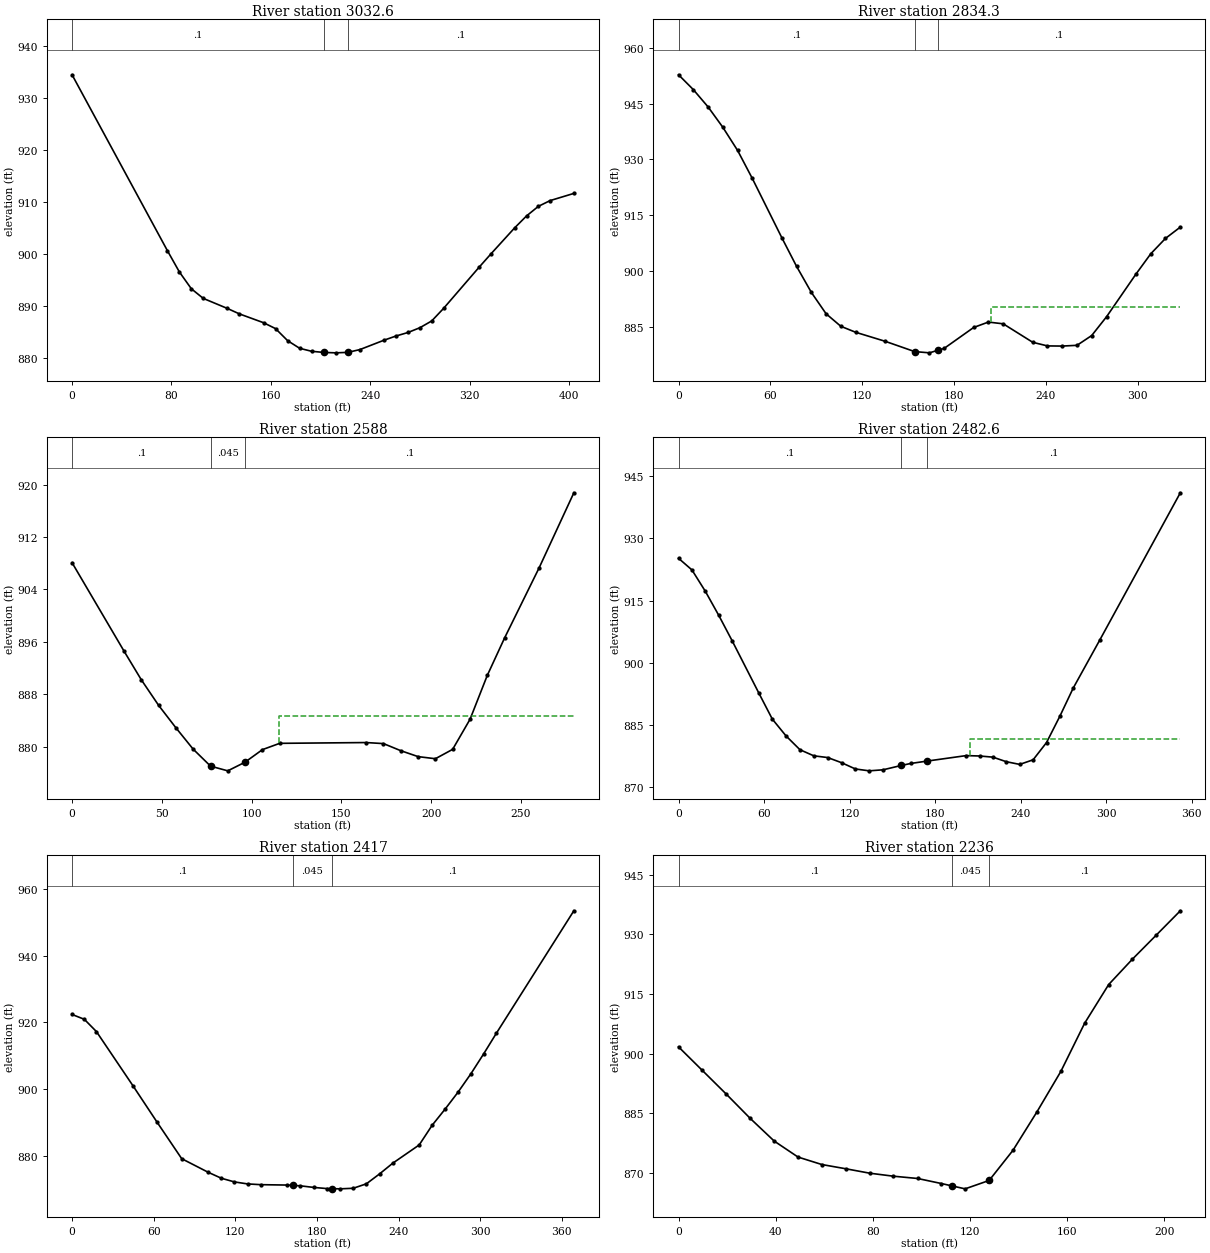
Type RM Length L Ch R = 1 ,3032.6  ,229.1,198.3,165.8
XS GIS Cut Line= 4
     1877736.762      447378.437     1877790.531      447469.309
     1877709.294      447612.721     1877750.492      447739.708
#Sta/Elev= 29
       0  934.41    76.8  900.59    86.4  896.52      96   893.3   105.6  891.45
     125  889.52   134.7  888.47   154.1  886.78   163.8  885.64   173.5  883.33
   183.2  881.86   192.8  881.29   202.5  881.07   212.2  880.99   221.9  881.08
   231.6  881.61     251  883.41   260.7  884.22   270.4   884.9     280  885.82
   289.5  887.12     299  889.52   327.6  897.43   337.2  900.01   356.2  904.99
   365.8  907.29   375.3  909.13   384.8  910.24   403.9  911.62
#Mann= 3 , 0 , 0
       0      .1       0   202.5    .045       0   221.9      .1       0
Bank Sta=202.5,221.9
XS Rating Curve= 0 ,0
Exp/Cntr=0.3,0.1

Type RM Length L Ch R = 1 ,2834.3  ,249,246.3,243.1
XS GIS Cut Line= 2
       1877490.5      447514.816     1877642.349      447805.294
#Sta/Elev= 30
       0  952.72     9.6  948.76    19.3  944.08    28.9  938.63    38.6  932.37
    48.2  924.85    67.5   908.9    77.1  901.23    86.8   894.2    96.4  888.48
     106  885.12   115.7  883.51     135  881.08   154.2  878.32   163.9  877.98
   169.6  878.69   173.5  879.17   192.8   884.8   202.4  886.25   212.1  885.78
   231.4  880.81     241  879.84   250.6   879.8   260.3     880   269.9  882.63
   279.6  887.68   298.8  899.14   308.5  904.61   318.1  908.74   327.8  911.78
#Mann= 3 , 0 , 0
       0      .1       0   154.2    .045       0   169.6      .1       0
#XS Ineff= 2 , 0
                          203.91          890.43
Permanent Ineff=
       F       F
Bank Sta=154.2,169.6
XS Rating Curve= 0 ,0
Exp/Cntr=0.3,0.1

Type RM Length L Ch R = 1 ,2588    ,128.4,105.3,81
XS GIS Cut Line= 2
     1877291.815      447653.214     1877451.902      447882.147
#Sta/Elev= 23
       0  908.09    28.9   894.6    38.5  890.23    48.2   886.3    57.8  882.88
    67.4  879.62    77.1  877.02    77.6  876.98    86.7   876.3    96.3  877.62
     106  879.54   115.6   880.5   163.8  880.62   173.4  880.46     183  879.38
   192.7  878.47   202.3  878.15   211.9  879.58   221.6  884.18   231.2  890.88
   240.8  896.58   260.1  907.33   279.4  918.77
#Mann= 3 , 0 , 0
       0      .1       0    77.6    .045       0    96.3      .1       0
#XS Ineff= 2 , 0
                          115.38           884.6
Permanent Ineff=
       F       F
Bank Sta=77.6,96.3
XS Rating Curve= 0 ,0
Exp/Cntr=0.3,0.1

Type RM Length L Ch R = 1 ,2482.6  ,62.1,65.7,70.4
XS GIS Cut Line= 4
     1877149.233      447728.394     1877183.064      447784.823
     1877319.013       447789.11     1877387.104      447923.055
#Sta/Elev= 29
       0   925.2     9.4   922.4    18.8  917.25    28.2  911.46    37.6  905.33
    56.4  892.68    65.8  886.44    75.5  882.36    85.2  879.06    94.9  877.59
   104.7  877.17   114.4  875.93   124.1  874.42   133.8  873.97   143.5  874.22
 156.273875.2626     163  875.75 174.658876.3348   201.8  877.64   211.2  877.55
   220.6  877.27     230  876.17   239.4  875.52   248.8  876.63   258.2  880.78
   267.6  887.15   276.9  893.89   295.7  905.57   352.1  940.99
#Mann= 3 , 0 , 0
       0      .1       0 156.273    .045       0 174.658      .1       0
#XS Ineff= 2 , 0
                          204.29          881.53
Permanent Ineff=
       F       F
Bank Sta=156.273,174.658
XS Rating Curve= 0 ,0
Skew Angle= 40
Exp/Cntr=0.3,0.1

Type RM Length L Ch R = 1 ,2417    ,157,181,204.9
XS GIS Cut Line= 4
      1877071.28      447761.357     1877111.694      447831.032
     1877285.259      447850.745     1877334.095      447953.346
#Sta/Elev= 30
       0  922.37       9  920.93    17.9  917.25    44.8  900.98    62.6  890.02
    80.6  879.14     100  875.08   109.7  873.28   119.4  872.17   129.1  871.57
   138.8  871.35   158.2  871.23   162.2871.1351   167.9     871   177.6  870.53
   187.3  870.18   191.3 870.147     197   870.1   206.7  870.27   216.4  871.61
   226.1  874.59   235.8   877.8   255.2  883.26   264.7  889.15   274.2  893.98
   283.6     899   293.1  904.53   302.6  910.57     312  916.79   368.9  953.46
#Mann= 3 , 0 , 0
       0      .1       0   162.2    .045       0   191.3      .1       0
Bank Sta=162.2,191.3
XS Rating Curve= 0 ,0
Exp/Cntr=0.3,0.1

Type RM Length L Ch R = 1 ,2236    ,191.4,192.4,193.3
XS GIS Cut Line= 2
     1877024.591      447813.002     1877113.133      447999.634
#Sta/Elev= 24
       0   901.7     9.8  895.77    19.7  889.78    29.5   883.7    39.4  877.98
    49.2  873.96      59  872.08    68.9  871.01    78.7   869.9    88.5  869.14
    98.4  868.57   108.2   867.3   112.5  866.71     118  865.96   127.5  867.99
   127.9  868.08   137.7  875.66   147.6  885.37   157.4  895.51   167.2  907.65
   177.1  917.39   186.9   923.8   196.7  929.84   206.6  935.96
#Mann= 3 , 0 , 0
       0      .1       0   112.5    .045       0   127.9      .1       0
Bank Sta=112.5,127.9
XS Rating Curve= 0 ,0
Exp/Cntr=0.3,0.1

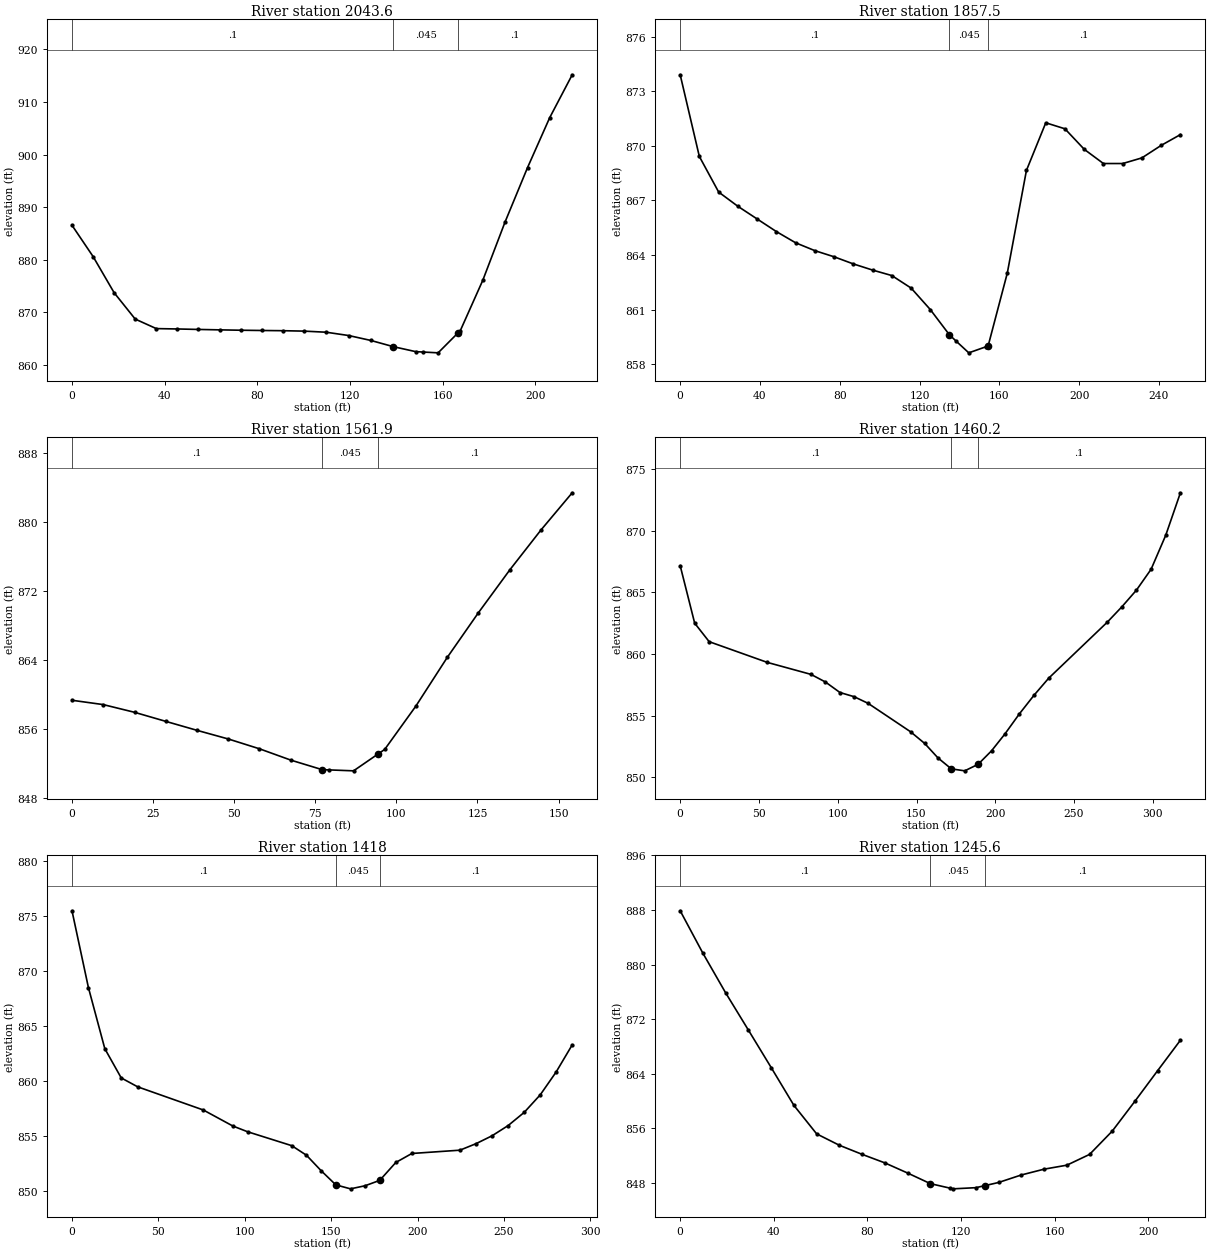
Type RM Length L Ch R = 1 ,2043.6  ,175.3,186,197
XS GIS Cut Line= 3
     1876858.678      447858.875     1876884.199       447955.75
     1876928.991      448062.521
#Sta/Elev= 26
       0  886.56     9.1  880.62    18.2  873.73    27.3  868.72    36.4  866.91
    45.5  866.84    54.6  866.75    63.8  866.67    72.9   866.6      82  866.55
    91.1  866.51   100.2  866.43   109.8  866.22   119.5  865.59   129.1  864.65
   138.8  863.47   148.4  862.53   151.7  862.45   158.1   862.3   166.7   866.1
   167.7  866.54   177.4  876.11     187  887.18   196.7  897.52   206.3  907.04
     216  915.18
#Mann= 3 , 0 , 0
       0      .1       0   138.8    .045       0   166.7      .1       0
Bank Sta=138.8,166.7
XS Rating Curve= 0 ,0
Exp/Cntr=0.3,0.1

Type RM Length L Ch R = 1 ,1857.5  ,282.5,295.6,308.1
XS GIS Cut Line= 2
     1876732.073      447879.151      1876715.19      448129.395
#Sta/Elev= 29
       0  873.91     9.6  869.42    19.3  867.46    28.9  866.68    38.6  865.98
    48.2  865.29    57.9  864.67    67.5  864.24    77.2   863.9    86.8  863.51
    96.5  863.17   106.1  862.87   115.8  862.18   125.4     861     135  859.61
   138.2  859.28   144.7  858.62   153.2  858.95   154.4     859     164     863
   173.6  868.65   183.3  871.27   192.9  870.94   202.6  869.81   212.2  869.03
   221.9  869.03   231.5  869.34   241.2  870.03   250.8  870.62
#Mann= 3 , 0 , 0
       0      .1       0     135    .045       0   154.4      .1       0
Bank Sta=135,154.4
XS Rating Curve= 0 ,0
Exp/Cntr=0.3,0.1

Type RM Length L Ch R = 1 ,1561.9  ,74.5,101.7,125.2
XS GIS Cut Line= 2
     1876491.124      447920.476     1876398.986      448044.177
#Sta/Elev= 19
       0  859.32     9.6  858.82    19.3  857.92    28.9  856.87    38.6  855.82
    48.2  854.82    57.8  853.68    67.5  852.36    77.1  851.26    79.2  851.23
    86.8  851.12    94.2  853.04    96.4  853.61     106  858.64   115.7  864.31
   125.3   869.5     135  874.49   144.6  879.12   154.2  883.43
#Mann= 3 , 0 , 0
       0      .1       0    77.1    .045       0    94.2      .1       0
Bank Sta=77.1,94.2
XS Rating Curve= 0 ,0
Exp/Cntr=0.3,0.1

Type RM Length L Ch R = 1 ,1460.2  ,43.6,42.2,37.2
XS GIS Cut Line= 5
      1876511.36      447845.012     1876461.106        447933.1
     1876411.767      447911.741     1876361.807      447902.239
     1876277.017      447974.528
#Sta/Elev= 26
       0  867.16     9.2   862.5    18.4     861    55.3  859.32      83  858.35
    92.2  857.73   101.4  856.88   110.4  856.54   119.3     856   146.2   853.7
   155.2  852.75   163.6  851.58   172.1  850.69   180.6  850.53   189.1  851.06
   197.6  852.15     206   853.5   215.3  855.15   224.6  856.66   233.9  858.04
     271  862.57   280.3  863.82   289.6  865.18   298.9  866.87   308.2  869.63
   317.5  873.07
#Mann= 3 , 0 , 0
       0      .1       0   172.1    .045       0   189.1      .1       0
Bank Sta=172.1,189.1
XS Rating Curve= 0 ,0
Exp/Cntr=0.3,0.1

Type RM Length L Ch R = 1 ,1418    ,201.8,172.4,149.1
XS GIS Cut Line= 5
     1876489.112      447824.243     1876453.603      447891.482
     1876406.029      447872.527     1876356.068      447863.025
     1876271.279      447935.314
#Sta/Elev= 25
       0   875.5     9.5  868.51      19  862.94    28.5  860.28      38  859.47
      76  857.36    93.1   855.9   101.6  855.38   127.2  854.11   135.7  853.24
   144.2  851.83   152.7  850.54   161.2  850.18   169.6  850.46   178.1  850.95
   187.4  852.58   196.7   853.4   224.5   853.7   233.8  854.29   243.1  855.01
   252.4  855.94   261.7  857.14     271  858.74   280.2  860.82   289.5  863.29
#Mann= 3 , 0 , 0
       0      .1       0   152.7    .045       0   178.1      .1       0
Bank Sta=152.7,178.1
XS Rating Curve= 0 ,0
Exp/Cntr=0.3,0.1

Type RM Length L Ch R = 1 ,1245.6  ,170.9,169.1,167.4
XS GIS Cut Line= 2
     1876279.416      447704.734     1876179.416      447893.623
#Sta/Elev= 25
       0  887.89     9.7  881.67    19.4  875.87    29.1  870.42    38.9  864.89
    48.6  859.35    58.3  855.18      68  853.51    77.7  852.18    87.4  850.93
    97.2  849.43   106.9  847.88   115.3  847.22   116.6  847.12   126.3  847.29
   130.3   847.6     136  848.05   145.7  849.15   155.4     850   165.2  850.59
   174.9  852.17   184.6  855.59   194.3  859.98     204  864.46   213.7  868.91
#Mann= 3 , 0 , 0
       0      .1       0   106.9    .045       0   130.3      .1       0
Bank Sta=106.9,130.3
XS Rating Curve= 0 ,0
Exp/Cntr=0.3,0.1

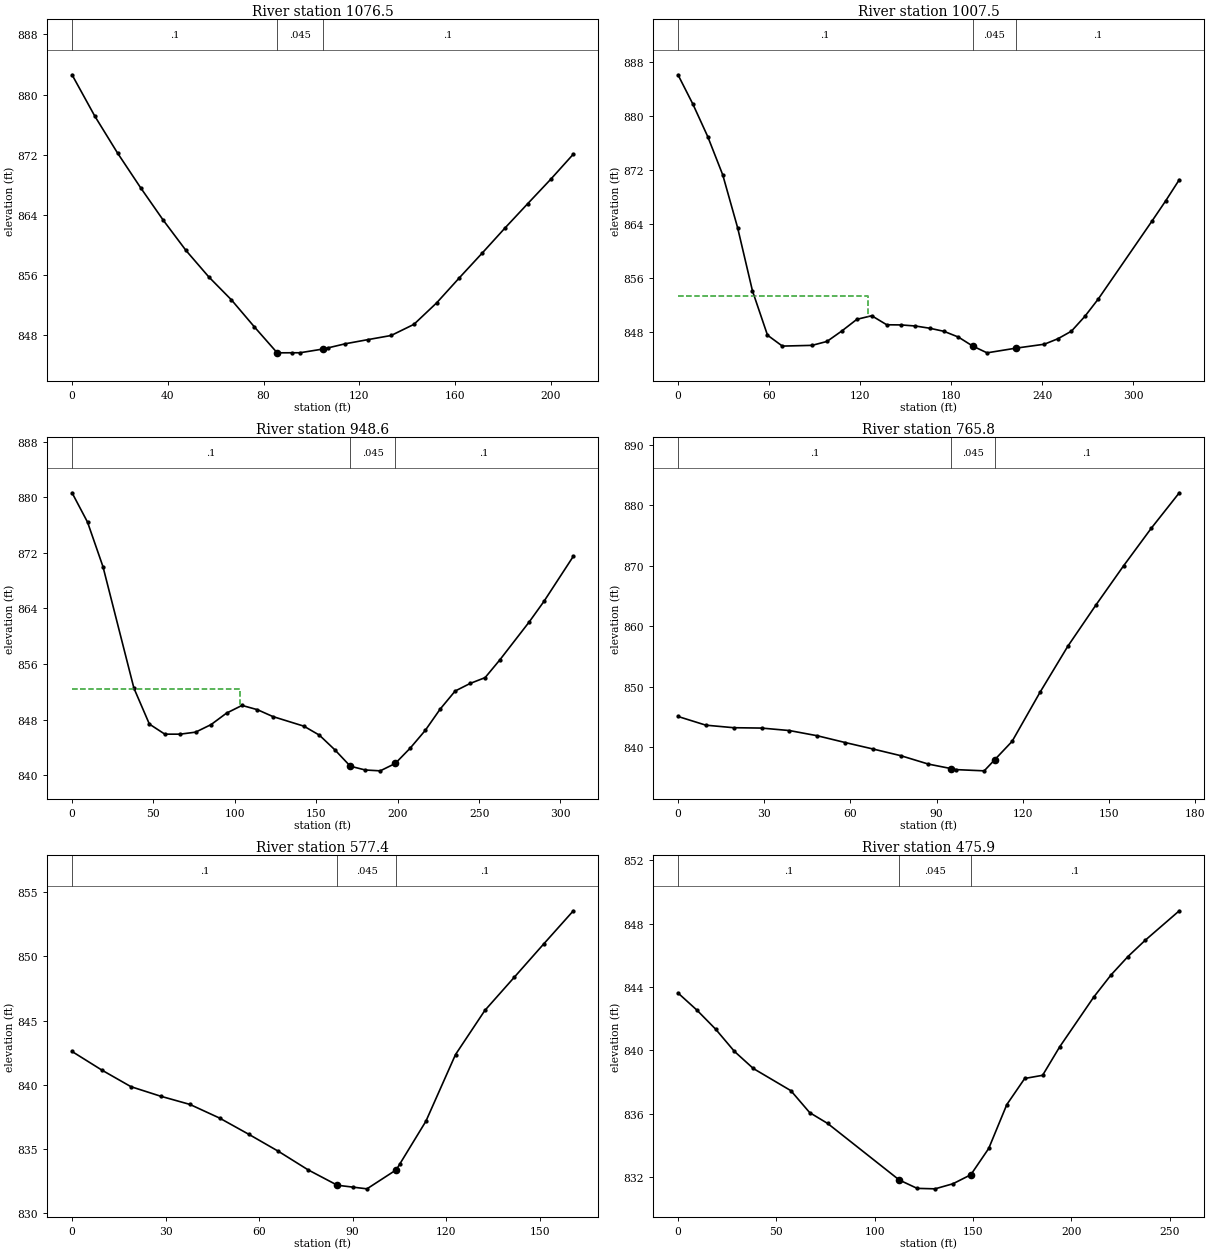
Type RM Length L Ch R = 1 ,1076.5  ,112.2,69,34.4
XS GIS Cut Line= 2
     1876105.897      447657.273     1876022.648      447849.455
#Sta/Elev= 25
       0  882.63     9.5  877.13      19  872.22    28.6  867.62    38.1  863.28
    47.6  859.25    57.1  855.74    66.6  852.67    76.2  849.07    85.7  845.63
    91.9  845.64    95.2  845.64   104.7  846.13   106.9  846.29   114.2  846.84
   123.8   847.4   133.3  847.94   142.8  849.42   152.3  852.28   161.8  855.62
   171.4  858.93   180.9  862.26   190.4   865.5   199.9  868.71   209.4  872.07
#Mann= 3 , 0 , 0
       0      .1       0    85.7    .045       0   104.7      .1       0
Bank Sta=85.7,104.7
XS Rating Curve= 0 ,0
Exp/Cntr=0.3,0.1

Type RM Length L Ch R = 1 ,1007.5  ,52.8,58.9,50
XS GIS Cut Line= 4
      1875884.83      447594.681     1875924.492      447726.387
     1876023.945      447756.569      1876016.34      447845.115
#Sta/Elev= 30
       0  886.13     9.8  881.79    19.6  876.97    29.5  871.29    39.3  863.46
    49.1  854.08      59  847.52    68.8   845.9    88.4  846.01    98.2  846.59
   108.1  848.16   117.9  849.87   127.7   850.4   137.6  849.06     147  849.04
   156.4  848.88   165.9  848.55   175.3  848.09   184.8  847.24   194.2  845.91
   203.7   844.9   222.6  845.59   241.5  846.18   250.4  846.99   259.3  848.11
   268.1  850.29     277  852.88   312.6   864.5   321.5  867.46   330.4  870.57
#Mann= 3 , 0 , 0
       0      .1       0   194.2    .045       0   222.6      .1       0
#XS Ineff= 2 , 0
          125.44  853.38
Permanent Ineff=
       F       F
Bank Sta=194.2,222.6
XS Rating Curve= 0 ,0
Skew Angle= 45
Exp/Cntr=0.3,0.1

Type RM Length L Ch R = 1 ,948.6   ,148.7,182.8,222.7
XS GIS Cut Line= 4
     1875864.865      447607.701      1875922.29      447768.639
     1876001.526      447792.685     1875997.185      447846.702
#Sta/Elev= 30
       0  880.65     9.5  876.43      19  870.01      38  852.52    47.5  847.35
      57   845.9    66.4   845.9    75.9  846.19    85.4  847.28    94.9  848.93
   104.4  850.04   113.9  849.42   123.4  848.43   142.4  847.05   151.9  845.76
   161.4  843.65   170.9  841.29   180.1  840.74   189.3  840.62   198.5  841.68
   207.7  843.89   216.9  846.43   226.1  849.51   235.3  852.11   244.5   853.2
   253.7  854.04   262.7  856.58   280.8  862.06   289.8     865   307.9  871.51
#Mann= 3 , 0 , 0
       0      .1       0   170.9    .045       0   198.5      .1       0
#XS Ineff= 2 , 0
          103.08  852.44
Permanent Ineff=
       F       F
Bank Sta=170.9,198.5
XS Rating Curve= 0 ,0
Skew Angle= 45
Exp/Cntr=0.3,0.1

Type RM Length L Ch R = 1 ,765.8   ,179.2,188.4,197.5
XS GIS Cut Line= 2
     1875796.067      447661.878     1875749.527      447830.037
#Sta/Elev= 21
       0  845.11     9.7  843.67    19.4  843.25    29.1  843.19    38.8  842.78
    48.5  841.92    58.2   840.8    67.8  839.74    77.6  838.62    87.2  837.23
    95.2  836.48    96.9  836.32   106.6  836.12   110.2  837.93   116.3  840.99
     126  849.09   135.7  856.72   145.4  863.48   155.1  870.01   164.8  876.26
   174.5  882.09
#Mann= 3 , 0 , 0
       0      .1       0    95.2    .045       0   110.2      .1       0
Bank Sta=95.2,110.2
XS Rating Curve= 0 ,0
Exp/Cntr=0.3,0.1

Type RM Length L Ch R = 1 ,577.4   ,63.4,101.5,144.9
XS GIS Cut Line= 2
     1875660.946        447610.7     1875560.252      447736.047
#Sta/Elev= 20
       0   842.6     9.5  841.16    18.9  839.86    28.4  839.12    37.8  838.48
    47.3  837.42    56.8  836.14    66.2  834.83    75.7  833.39    85.1  832.19
    90.2  832.04    94.6  831.91     104  833.39   105.2  833.87   113.5  837.17
     123  842.36   132.4  845.79   141.9  848.39   151.3  850.97   160.8  853.55
#Mann= 3 , 0 , 0
       0      .1       0    85.1    .045       0     104      .1       0
Bank Sta=85.1,104
XS Rating Curve= 0 ,0
Exp/Cntr=0.3,0.1

Type RM Length L Ch R = 1 ,475.9   ,83.1,85.5,79.6
XS GIS Cut Line= 4
      1875643.42      447588.136      1875592.77      447631.999
     1875478.826      447599.979     1875432.656      447652.025
#Sta/Elev= 23
       0  843.62     9.6  842.54    19.1  841.34    28.7  839.93    38.3  838.85
    57.4  837.45      67  836.06    76.1  835.38   112.5  831.81   121.6  831.28
   130.7  831.25   139.8  831.57   148.9  832.14     158   833.8   167.2  836.57
   176.3  838.22   185.4  838.42   194.1  840.22   211.4  843.36   220.2  844.76
   228.8  845.92   237.5  846.94   254.9  848.81
#Mann= 3 , 0 , 0
       0      .1       0   112.5    .045       0   148.9      .1       0
Bank Sta=112.5,148.9
XS Rating Curve= 0 ,0
Exp/Cntr=0.3,0.1

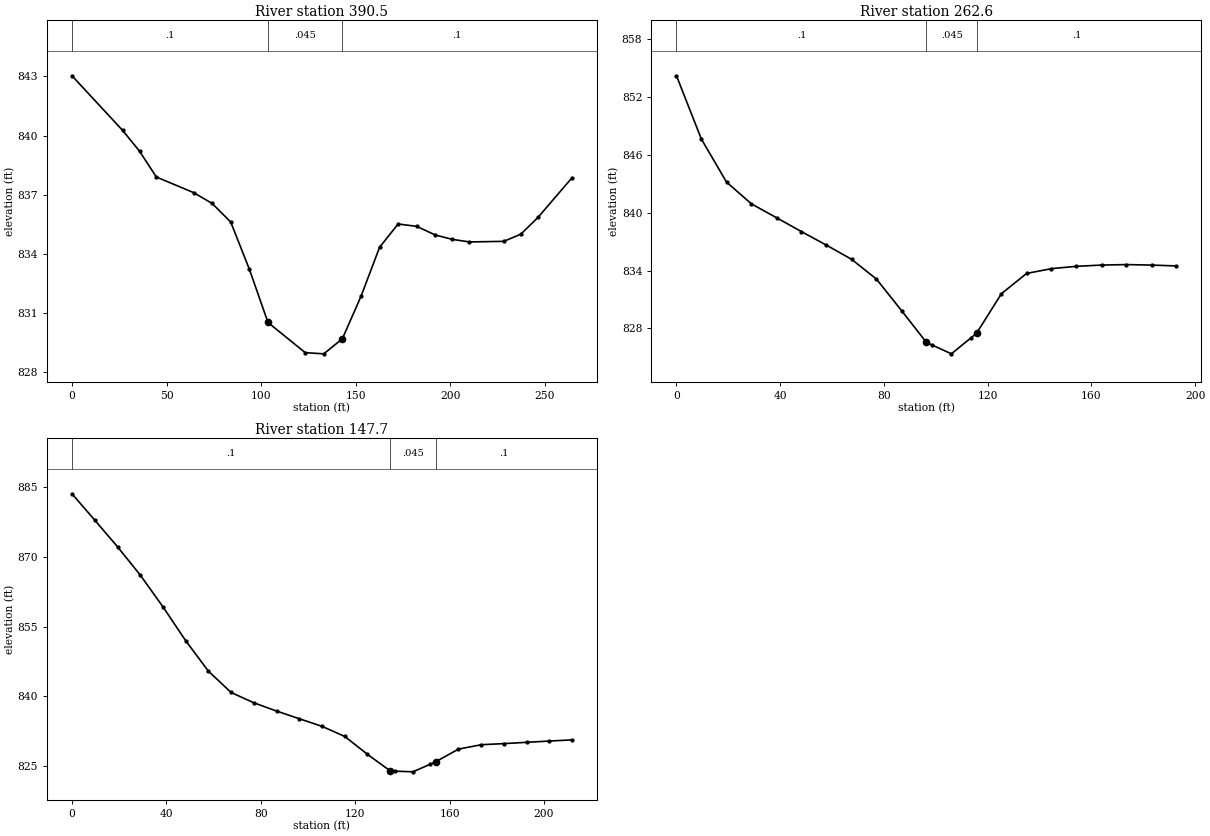
Type RM Length L Ch R = 1 ,390.5   ,161,127.9,97.4
XS GIS Cut Line= 4
     1875580.994      447545.094     1875548.058      447575.183
     1875406.065      447535.388     1875354.531      447586.053
#Sta/Elev= 23
       0  843.03    26.8  840.26    35.7  839.21    44.6   837.9    64.3  837.11
    74.1  836.56    83.9  835.62    93.8  833.22   103.6  830.53   123.3     829
   133.1  828.94   142.9   829.7   152.8  831.86   162.6  834.34   172.4  835.52
   182.2   835.4   192.1  834.96   201.1  834.74   210.1  834.61   228.2  834.64
   237.2     835   246.3  835.85   264.3  837.86
#Mann= 3 , 0 , 0
       0      .1       0   103.6    .045       0   142.9      .1       0
Bank Sta=103.6,142.9
XS Rating Curve= 0 ,0
Exp/Cntr=0.3,0.1

Type RM Length L Ch R = 1 ,262.6   ,115.9,114.8,113.9
XS GIS Cut Line= 2
     1875481.681      447393.618     1875319.876      447498.479
#Sta/Elev= 23
       0  854.21     9.6  847.64    19.3  843.18    28.9  840.92    38.6  839.48
    48.2  838.04    57.8  836.64    67.5  835.17    77.1  833.12    86.8  829.84
    96.4  826.54    98.7  826.26     106  825.36   113.7  827.05   115.7  827.49
   125.3   831.6     135   833.7   144.6   834.2   154.2  834.44   163.9  834.57
   173.5  834.62   183.2  834.57   192.8  834.48
#Mann= 3 , 0 , 0
       0      .1       0    96.4    .045       0   115.7      .1       0
Bank Sta=96.4,115.7
XS Rating Curve= 0 ,0
Exp/Cntr=0.3,0.1

Type RM Length L Ch R = 1 ,147.7   ,148.5,147.7,146.6
XS GIS Cut Line= 2
     1875445.977      447272.496     1875273.376      447395.457
#Sta/Elev= 25
       0  883.52     9.6  877.89    19.3  872.14    28.9  866.09    38.5  859.29
    48.2  851.97    57.8  845.45    67.4  840.87    77.1  838.64    86.7  836.87
    96.3  835.23     106  833.58   115.6  831.42   125.2  827.59   134.9  824.01
   136.9  823.97   144.5  823.82   151.9  825.48   154.1  825.97   163.8   828.7
   173.4  829.64     183  829.88   192.7  830.16   202.3  830.43   211.9  830.68
#Mann= 3 , 0 , 0
       0      .1       0   134.9    .045       0   154.1      .1       0
Bank Sta=134.9,154.1
XS Rating Curve= 0 ,0
Exp/Cntr=0.3,0.1

Chan Stop Cuts=-1
Use User Specified Reach Order=0
Composite Channel Slope=5